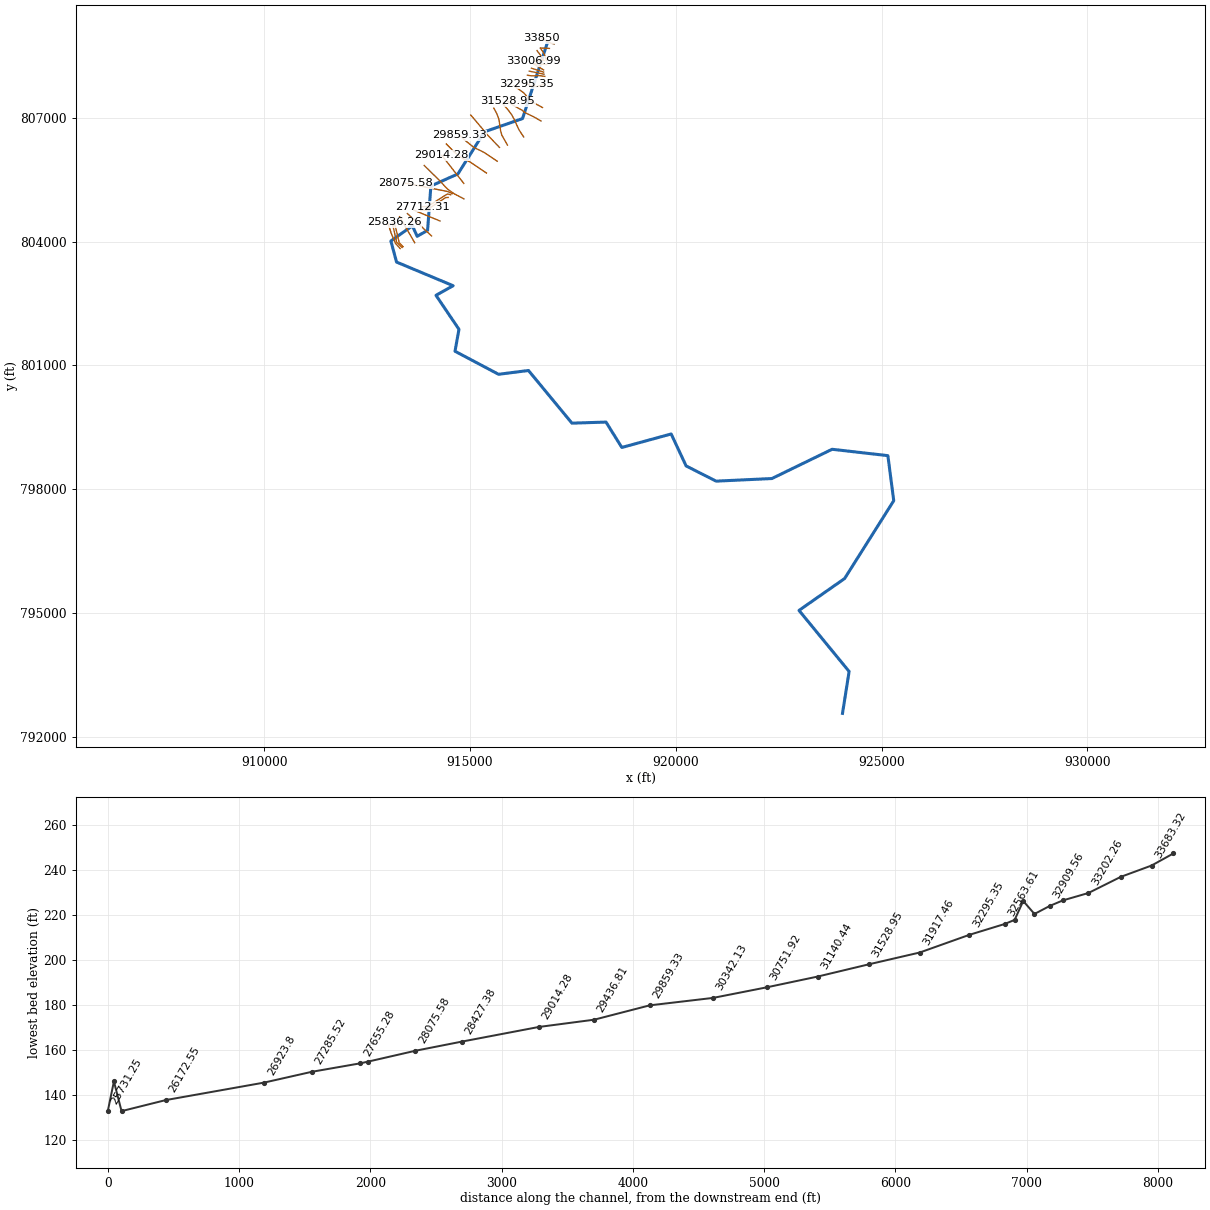
--- 13252_ras.prj (project) ---

Proj Title=13252
Current Plan=p01
Default Exp/Contr=0.3,0.1
English Units
Geom File=g01
Flow File=f01
Plan File=p01
Y Axis Title=Elevation
X Axis Title(PF)=Main Channel Distance
X Axis Title(XS)=Station
BEGIN DESCRIPTION:
RFD model 13252 exported to HEC-RAS
END DESCRIPTION:

--- 13252_ras.p01 (plan) ---

Plan Title=Plan 01
Program Version=4.10
Short Identifier=Plan 01
Geom File=g01
Flow File=f01
Subcritical Flow
Calc Critical at every XS
Secant Critical Depth

--- 13252_ras.f01 (steady flow) ---

Flow Title=Flow 01
Program Version=5.01
Number of Profiles= 6
Profile Names=10yr,25yr,50yr,100yr,100plus,500yr
River Rch & RM=13252,60,   33850
  416.78  1059.2  788.89 1031.47 1246.33 1642.75
River Rch & RM=13252,60,33683.32
  420.27 1066.75  795.64 1040.38  1257.1 1657.86
River Rch & RM=13252,60,33448.23
  427.92 1083.27  810.47 1059.94 1280.73 1691.02
River Rch & RM=13252,60,33006.99
  518.75 1276.45  986.99 1293.05  1562.4 2089.07
River Rch & RM=13252,60,32909.56
  524.71 1288.95   998.6  1308.4 1580.95 2115.46
River Rch & RM=13252,60,32791.15
  529.33 1298.63 1007.62 1320.31 1595.34 2135.95
River Rch & RM=13252,60,32705.66
  533.95 1308.28 1016.61 1332.21 1609.71 2156.41
River Rch & RM=13252,60,32640.14
  535.92  1312.4 1020.46  1337.3 1615.87 2165.18
River Rch & RM=13252,60,32295.35
  547.74 1337.04 1043.51 1367.77 1652.68 2217.67
River Rch & RM=13252,60,31917.46
 1267.72 2734.31 2463.71  3253.9  3931.7  5573.8
River Rch & RM=13252,60,31528.95
 1344.18 2874.27 2615.92 3456.76 4176.82 5944.04
River Rch & RM=13252,60,31140.44
  1362.2  2907.1 2651.84 3504.65 4234.68 6031.64
River Rch & RM=13252,60,30751.92
 1388.08 2954.13 2703.43 3573.44  4317.8 6157.62
River Rch & RM=13252,60,30342.13
 1528.25 3206.61 2983.21 3946.69 4768.81 6843.77
River Rch & RM=13252,60,29859.33
 1644.73 3413.83 3216.18 4257.74 5144.65 7418.73
River Rch & RM=13252,60,29436.81
 1800.59 3687.77 3528.53 4675.06  5648.9 8194.31
River Rch & RM=13252,60,29014.28
 1851.51 3776.49 3630.71 4811.66 5813.96 8449.15
River Rch & RM=13252,60,28427.38
  1902.1 3864.29 3732.31 4947.51  5978.1 8703.05
River Rch & RM=13252,60,28075.58
 2070.31  4153.8 4070.55 5400.02 6524.87  9551.9
River Rch & RM=13252,60,27712.31
 2108.63 4219.26  4147.7 5503.29 6649.65 9746.25
River Rch & RM=13252,60,27655.28
 2131.55 4258.32 4193.85 5565.06 6724.29 9862.64
River Rch & RM=13252,60,27285.52
 2142.51 4276.98 4215.93 5594.62    6760 9918.35
River Rch & RM=13252,60, 26923.8
 2162.01 4310.15 4255.22 5647.23 6823.5710017.56
River Rch & RM=13252,60,26172.55
 2178.63 4338.38 4288.71 5692.06 6877.7410102.15
River Rch & RM=13252,60,25836.26
 2200.43 4375.35 4332.64 5750.88 6948.82 10213.2
River Rch & RM=13252,60,25731.25
    2225 4416.98 4382.19 5817.24 7028.9910338.56
River Rch & RM=13252,60,25342.87
 2262.22  4479.9 4457.25 5917.76 7150.4610528.65
River Rch & RM=13252,60,24775.41
 2287.11 4521.89 4507.46 5985.02 7231.7210655.93
River Rch & RM=13252,60,24205.38
 2318.02 4573.93 4569.82 6068.56 7332.6710814.19
River Rch & RM=13252,60,23639.38
 2343.24 4616.31 4620.72 6136.76 7415.0710943.45
River Rch & RM=13252,60,22719.03
 2367.92 4657.75 4670.56 6203.54 7495.7711070.14
River Rch & RM=13252,60,22113.95
 2436.09 4771.81 4808.24 6388.05 7718.71 11420.6
River Rch & RM=13252,60,21624.41
  2791.2 5358.78 5526.96 7351.96 8883.4113261.52
River Rch & RM=13252,60,21017.69
 2828.75 5420.18 5603.09 7454.13 9006.8613457.57
River Rch & RM=13252,60,20360.67
 2875.52 5496.49 5697.95 7581.45  9160.713702.15
River Rch & RM=13252,60,20121.28
 2883.52 5509.53 5714.18 7603.24 9187.0313744.02
River Rch & RM=13252,60,19881.88
 2907.04 5547.82 5761.91 7667.31 9264.4513867.22
River Rch & RM=13252,60,19642.49
 2992.78 5687.02 5935.94 7900.97 9546.7814317.04
River Rch & RM=13252,60, 19403.1
 3031.49 5749.66 6014.54 8006.52 9674.3214520.51
River Rch & RM=13252,60,19288.97
  3048.6 5777.32 6049.31 8053.21 9730.7314610.57
River Rch & RM=13252,60,19223.87
 3063.94  5802.1 6080.47 8095.07 9781.3114691.34
River Rch & RM=13252,60,18985.41
 3077.95 5824.71 6108.94  8133.3  9827.514765.13
River Rch & RM=13252,60,18572.25
  3132.1 5911.96 6218.98 8281.1210006.1115050.66
River Rch & RM=13252,60,18151.32
 3220.29 6053.57 6398.29 8522.0210297.1915516.67
River Rch & RM=13252,60,17743.29
 3255.75 6110.35 6470.42 8618.9510414.3215704.42
River Rch & RM=13252,60,17264.71
 3279.05 6147.62 6517.83 8682.6710491.3115827.91
River Rch & RM=13252,60,16875.16
 3291.55 6167.59 6543.27 8716.8510532.6115894.17
River Rch & RM=13252,60,16310.48
 3307.05 6192.34 6574.81 8759.2510583.8415976.39
River Rch & RM=13252,60,15249.54
 3654.46  6742.8 7282.75 9711.1611734.0417828.87
River Rch & RM=13252,60,14243.99
 3952.26 7208.51 7890.8710529.5212722.8719430.72
River Rch & RM=13252,60,12554.52
  4011.6 7300.67 8012.1710692.8212920.1819751.32
River Rch & RM=13252,60, 12436.4
 4014.47 7305.13 8018.0510700.7512929.7619766.89
River Rch & RM=13252,60,11928.92
 4051.45 7362.45 8093.6610802.5513052.7719966.92
River Rch & RM=13252,60,7935.333
 5881.9410117.1111854.8615876.0619183.1230069.67
River Rch & RM=13252,60, 2742.56
  8750.714195.0617803.74 23928.728913.1646515.83
River Rch & RM=13252,60,     509
 8877.33   1437018067.54 24286.429345.3747255.63
Boundary for River Rch & Prof#=13252,60,1
Up Type= 0
Dn Type= 2
Boundary for River Rch & Prof#=13252,60,2
Up Type= 0
Dn Type= 2
Boundary for River Rch & Prof#=13252,60,2
Up Type= 0
Dn Type= 2
Boundary for River Rch & Prof#=13252,60,2
Up Type= 0
Dn Type= 2
Boundary for River Rch & Prof#=13252,60,2
Up Type= 0
Dn Type= 2
Boundary for River Rch & Prof#=13252,60,2
Up Type= 0
Dn Type= 2

--- 13252_ras.g01 (geometry) ---

Geom Title=13252
Program Version=4.10

River Reach=13252,60
Reach XY= 30
916886.413977491808843.063204925916275.649550559806982.064935785
915349.338543001 806661.65633956914705.039199474805640.346396381
914048.072361737805348.114899112913967.935061605804271.798490024
913714.696916196804129.588943917913598.455686631804383.208125597
913076.133673638804015.256498695913214.234834552803503.873490636
914588.968599651 802930.96980564914172.443466011802698.374229319
914730.293647766801874.643060823914634.821105242801342.520451863
915692.867364082800784.164147009916419.785344779800875.945211354
  917475.6717836799599.577315113918303.213798168799625.780270523
918688.232187272799010.136635373 919887.09827328799337.731379156
920249.846506628798563.126917049920978.745722026798194.292078055
922334.576055142798257.484495994923797.133925557798966.656949679
925152.602675529798812.143060793925294.963786661797720.129171912
924100.311896118795832.648610858922993.140869976795061.101394147
924210.588786632793581.066671913924049.998508842792565.441671918

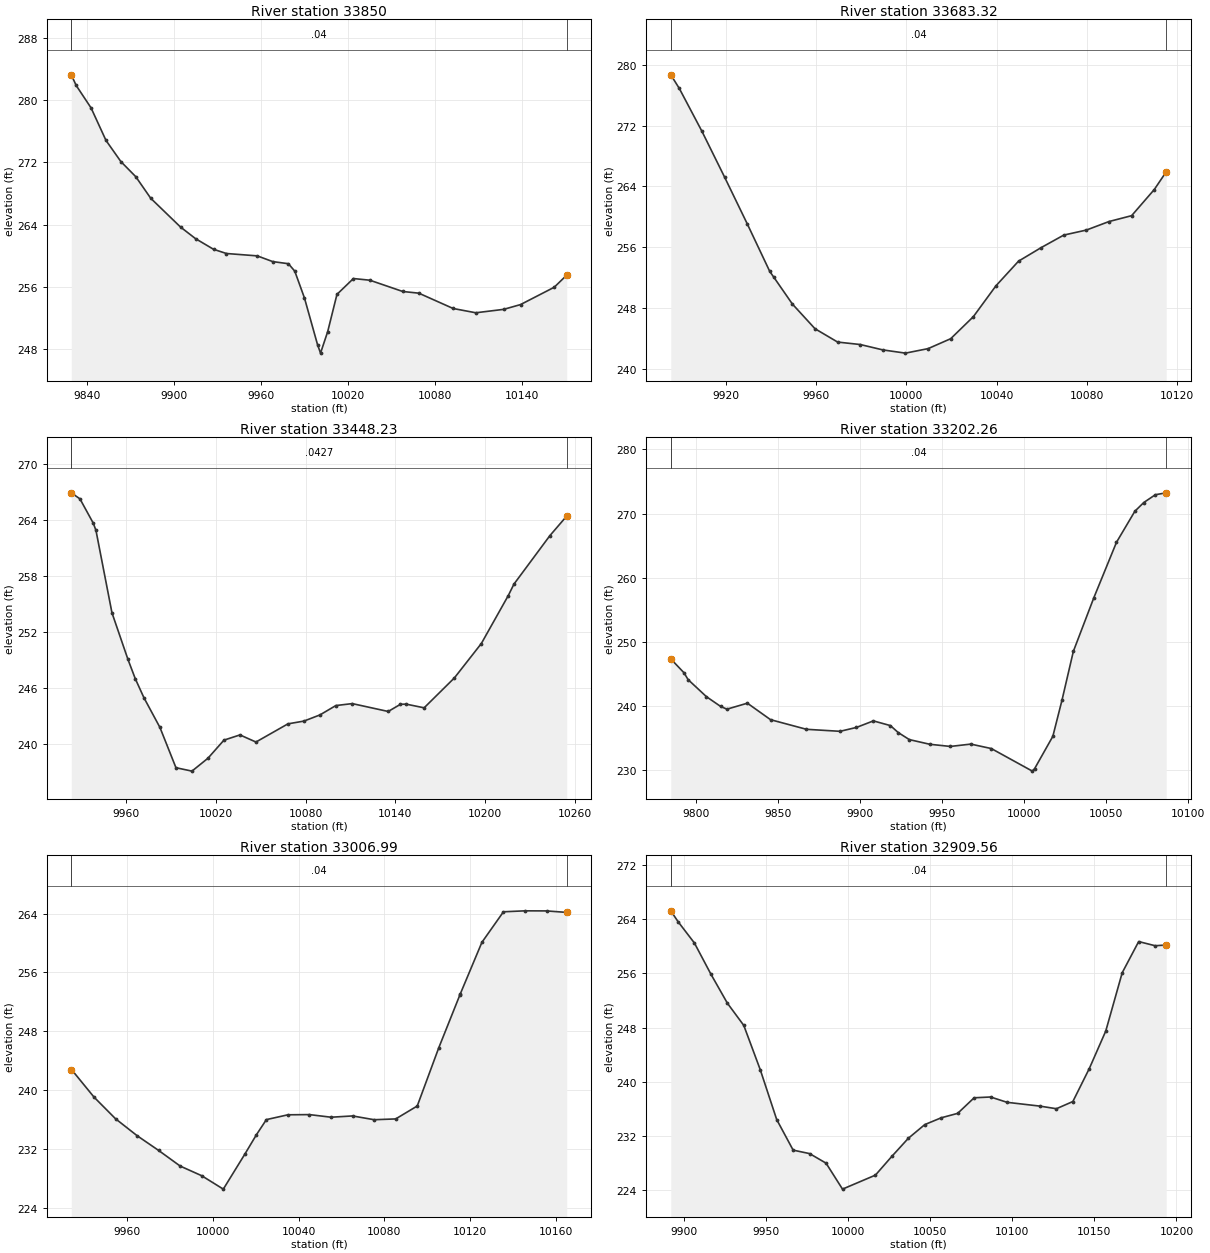
Type RM Length L Ch R = 1 ,   33850,166.672400,166.672400,166.672400
XS GIS Cut Line= 6
917048.262436446808790.445136444916967.527011371808809.822898375
916909.591190645808830.950785362916885.068949269808842.626284929
916832.786154484808870.638017105916737.564041885808926.906362344
#Sta/Elev= 30
9829.143283.27029832.498281.90469842.782279.01479853.066274.8371 9863.35272.1162
9873.634270.16969883.918267.40429904.486263.70169914.861262.20759927.282260.8393
 9936.15260.29919957.438259.99439968.082259.25979978.919 258.9869983.301258.0333
9989.984254.5858    9999248.593610001.08247.491110006.03250.259110012.42255.0455
10023.77257.080410035.11256.8653 10057.8 255.41610068.89255.199210092.59253.2287
 10108.2252.679110127.44253.118910139.05253.731910162.28255.957410170.92257.5154
#Mann= 3 , 0 , 0
9829.143    0.04       09829.143    0.04       010170.92    0.04       0
#XS Ineff= 2 , 0
       0                               0
Bank Sta=9829.143,10170.92
Exp/Cntr=0.3,0.1

Type RM Length L Ch R = 1 ,33683.32,235.098100,235.098100,235.098100
XS GIS Cut Line= 2
 916928.76336992808682.560151082916709.712889151808694.278901082
#Sta/Elev= 25
9895.771 278.676 9899.54276.88179909.555271.25339919.569265.24199929.583259.1134
9939.597252.82989941.443  252.059949.612248.54859959.626245.3037 9969.64243.5506
9979.655243.22939989.669242.52029999.683242.0978 10009.7242.689110019.71243.9943
10029.73246.884710039.74250.943310049.75254.184710059.77255.966410069.78 257.612
 10079.8258.273710089.81 259.39410099.83 260.16510109.84263.593210115.14265.9238
#Mann= 3 , 0 , 0
9895.771    0.04       09895.771    0.04       010115.14    0.04       0
#XS Ineff= 2 , 0
       0                               0
Bank Sta=9895.771,10115.14
Exp/Cntr=0.3,0.1

Type RM Length L Ch R = 1 ,33448.23,245.967200,245.967200,245.967200
XS GIS Cut Line= 4
916860.253754536808389.591401082 916807.97010069808526.610631851
916794.448466074808562.668324159916713.318658382808684.363035697
#Sta/Elev= 30
9923.165266.94919928.954266.29949937.902263.67289939.657 262.9119950.361254.0581
9961.064 249.0499965.952246.97839971.767244.92719982.471 241.7369993.174237.4135
10003.88237.046210014.58238.431710025.28240.375110035.99240.936710046.69240.1728
 10068.1 242.12610078.78242.422710089.46243.082210100.14244.090710111.13244.3019
10135.17243.455610143.39244.228910147.19 244.24410159.21243.849510179.45247.0625
10197.47250.7555 10215.5255.9087 10219.3257.142110243.34262.349810254.59264.4501
#Mann= 3 , 0 , 0
9923.165  0.0427       09923.165  0.0427       010254.59  0.0427       0
#XS Ineff= 2 , 0
       0                               0
Bank Sta=9923.165,10254.59
Exp/Cntr=0.3,0.1

Type RM Length L Ch R = 1 ,33202.26,195.270600,195.270600,195.270600
XS GIS Cut Line= 6
916794.448466074808391.394285697916763.799427613808406.718804928
916743.066254536808427.451978005916733.150389151808449.988035697
916725.037408382 808499.56736262916626.780196843808630.276497236
#Sta/Elev= 30
9784.329247.35949792.392245.18969794.893244.12749806.073241.47319814.752239.9492
9818.596239.5292 9831.04240.46199845.182237.89019867.088236.39299887.583236.0797
9897.605236.68579907.916237.70399918.301236.97099923.044235.8932 9929.84234.7896
9942.351234.06069954.861 233.7249967.372234.08849979.882233.3939 10004.9229.8781
10006.32230.279110017.41 235.30110022.96240.899810029.92 248.53310042.43 256.893
10056.24265.524410067.45270.359110072.89271.718610079.96272.933710086.57273.2281
#Mann= 3 , 0 , 0
9784.329    0.04       09784.329    0.04       010086.57    0.04       0
#XS Ineff= 2 , 0
       0                               0
Bank Sta=9784.329,10086.57
Exp/Cntr=0.3,0.1

Type RM Length L Ch R = 1 ,33006.99,97.429900,97.429900,97.429900
XS GIS Cut Line= 2
916775.518177613 808394.09861262916545.650389151808369.759670313
#Sta/Elev= 27
9933.923242.75869934.444242.6628  9944.5239.07789954.556236.13139964.612233.8343
9974.668231.82939984.724229.7058 9994.78228.393610004.84226.574510014.89231.3232
10020.33233.975410024.95236.0157   10035236.669510045.06236.695210055.12236.3408
10065.17 236.51410075.23235.999910085.28236.108510095.34 237.86410105.39245.7768
10115.31253.000710115.45253.105710125.51260.091410135.56264.239410145.62264.3704
10155.67264.358310165.08264.1564
#Mann= 3 , 0 , 0
9933.923    0.04       09933.923    0.04       010165.08    0.04       0
#XS Ineff= 2 , 0
       0                               0
Bank Sta=9933.923,10165.08
Exp/Cntr=0.3,0.1

Type RM Length L Ch R = 1 ,32909.56,118.412700,118.412700,118.412700
XS GIS Cut Line= 2
916859.352312228808294.038516467916558.270581459808309.363035697
#Sta/Elev= 30
9892.276265.20389896.633263.62469906.646 260.4579916.659255.87689926.672251.5996
9936.685248.31129946.698241.78999956.711234.43689966.724229.92569976.737 229.414
 9986.75228.00589996.763224.176810016.79226.2399 10026.8229.010210036.81231.6692
10046.83233.689810056.84234.693110066.85235.346110076.87237.642910086.88 237.759
10096.89236.975310116.92236.413710126.93236.029110136.94237.090110146.96241.9592
10156.97247.481410166.98256.0799   10177260.673910187.01260.058710193.75260.1635
#Mann= 3 , 0 , 0
9892.276    0.04       09892.276    0.04       010193.75    0.04       0
#XS Ineff= 2 , 0
       0                               0
Bank Sta=9892.276,10193.75
Exp/Cntr=0.3,0.1

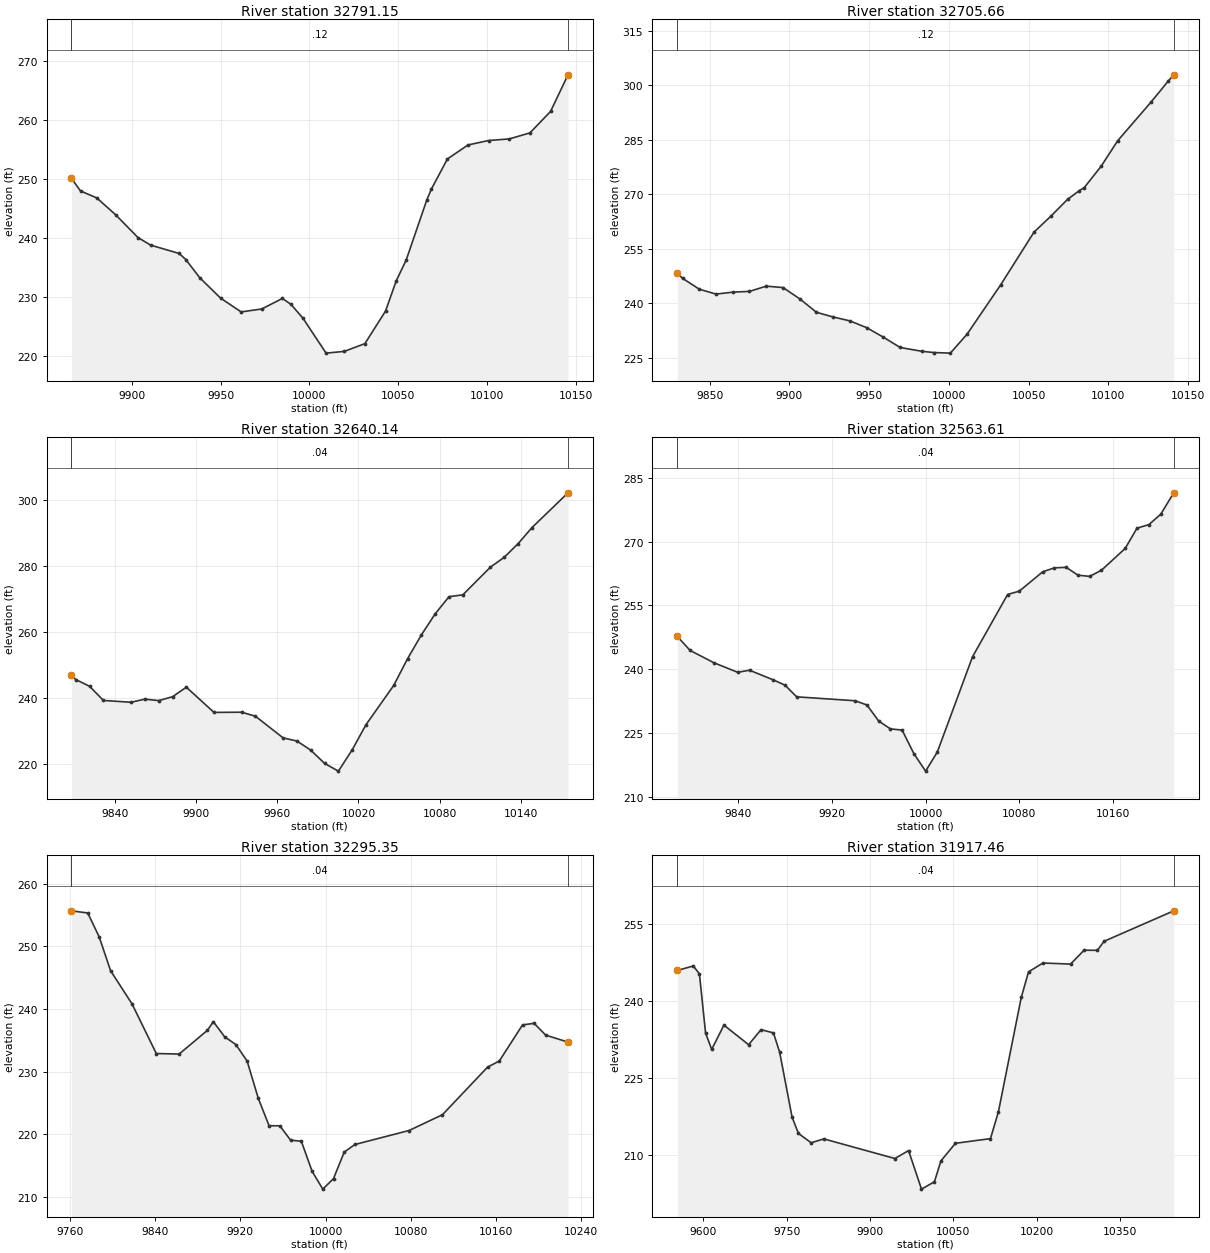
Type RM Length L Ch R = 1 ,32791.15,85.490100,85.490100,85.490100
XS GIS Cut Line= 2
916787.236927613808162.427939544916546.551831459808303.954381851
#Sta/Elev= 30
9866.185250.1305 9871.26 247.9949880.381246.82239890.988243.97099903.583240.1071
9910.717238.82229926.784237.41529930.445236.39299938.385233.28219949.985229.8734
9961.586227.52389973.187228.02329984.787229.80429989.631228.80279996.388226.4418
10009.36220.550410019.59 220.84610031.19  222.1610042.79227.664310048.82232.7845
10054.39236.289810065.99246.456510068.55248.297110077.59 253.41110089.19255.7804
10100.79256.5326 10112.4256.8024   10124257.8219 10135.6261.4525 10145.4267.6478
#Mann= 3 , 0 , 0
9866.185    0.12       09866.185    0.12       0 10145.4    0.12       0
#XS Ineff= 2 , 0
       0                               0
Bank Sta=9866.185,10145.4
Exp/Cntr=0.3,0.1

Type RM Length L Ch R = 1 ,32705.66,65.515800,65.515800,65.515800
XS GIS Cut Line= 2
 916788.13836992808108.341401082 916491.56385069 808202.99284339
#Sta/Elev= 30
9829.648248.27479832.942246.89469843.439243.89429853.936242.54529864.433243.0769
 9874.93243.29019885.427 244.7299895.924244.3462 9906.42241.24629916.917237.5387
9927.414236.24539937.911235.17899948.408233.31279958.905230.69229969.402227.8659
 9983.11226.81199990.396226.480910000.89226.313210011.39231.537210032.38245.0595
10053.38259.612810063.87263.951610074.37268.600710081.78271.000110084.87271.8451
10095.37277.667710105.86284.752610126.86295.423210137.35301.039910140.96302.8383
#Mann= 3 , 0 , 0
9829.648    0.12       09829.648    0.12       010140.96    0.12       0
#XS Ineff= 2 , 0
       0                               0
Bank Sta=9829.648,10140.96
Exp/Cntr=0.3,0.1

Type RM Length L Ch R = 1 ,32640.14,76.525900,76.525900,76.525900
XS GIS Cut Line= 2
916798.087622057808057.944098732916438.929635946808131.728820954
#Sta/Elev= 30
9808.053247.02749811.206245.63489821.414243.58429831.623239.30969852.041238.7548
 9862.25 239.7029872.459239.26129882.667 240.4329892.876243.31819913.294235.6841
9933.712235.75089943.921234.52789964.338227.97089974.547227.02619984.756224.2627
9994.965220.252710005.17217.917910015.38224.386710025.59232.001710046.01243.8462
10056.22251.931610066.43259.127110076.64265.520510086.84 270.71610097.05271.2632
10117.47279.662510127.68282.637710137.89286.7621 10148.1291.615410174.71302.1392
#Mann= 3 , 0 , 0
9808.053    0.04       09808.053    0.04       010174.71    0.04       0
#XS Ineff= 2 , 0
       0                               0
Bank Sta=9808.053,10174.71
Exp/Cntr=0.3,0.1

Type RM Length L Ch R = 1 ,32563.61,268.260200,268.260200,268.260200
XS GIS Cut Line= 6
916815.855511338808005.075953975 916692.78745941808023.068839376
 916642.78354027808023.836303922916525.250162909808017.492037881
916464.494314173808021.908758714916393.965682728 808033.15312629
#Sta/Elev= 30
9787.706247.7216 9798.73244.42679819.042 241.5419839.354239.29639849.509239.7857
9869.719237.52679879.773236.29369889.827233.53319939.951232.60749949.952231.6044
9959.953227.84069969.978 226.0049980.011225.71399990.043220.176610000.08216.0744
10010.12220.5799 10040.2242.9498 10070.2257.576910080.21258.374310100.26262.9193
10110.28263.844410120.31263.958110130.34262.116810140.36261.834610150.49263.2865
10170.74268.395210180.86273.167610190.99273.994610201.12276.424910212.29 281.468
#Mann= 3 , 0 , 0
9787.706    0.04       09787.706    0.04       010212.29    0.04       0
#XS Ineff= 2 , 0
       0                               0
Bank Sta=9787.706,10212.29
Exp/Cntr=0.3,0.1

Type RM Length L Ch R = 1 ,32295.35,377.891200,377.891200,377.891200
XS GIS Cut Line= 6
916819.224934853807825.609252966916657.411797054807764.516537675
916612.399071507807757.856236793916509.422842329807773.281034325
916456.705556029  807790.2001179916375.826083944807825.324084444
#Sta/Elev= 30
9761.449255.66119776.712255.31669787.441251.51059798.171246.10699818.311240.8108
9841.089232.90179862.548232.81689889.005236.58759894.658237.9805 9905.24235.5718
9915.823 234.3329926.405231.68819936.873225.74959946.982221.3886 9957.09221.3718
9967.199219.08479977.308218.90559987.381214.12669997.441211.2728 10007.5212.9513
10017.57 217.18110027.64218.392210078.46220.623210109.81  223.1410152.28230.7488
10163.19231.698910184.99237.460810195.89237.719810206.79235.8341 10227.7234.7231
#Mann= 3 , 0 , 0
9761.449    0.04       09761.449    0.04       0 10227.7    0.04       0
#XS Ineff= 2 , 0
       0                               0
Bank Sta=9761.449,10227.7
Exp/Cntr=0.3,0.1

Type RM Length L Ch R = 1 ,31917.46,388.514000,388.514000,388.514000
XS GIS Cut Line= 6
916761.167451947 807250.40154548916468.658279874807403.207986948
916423.680714405807445.158419953916358.543650428807546.114646907
 916300.01894077807610.766953588916059.071780462 807779.18619818
#Sta/Elev= 30
9553.036245.93159581.907246.8133 9592.94245.26299603.974233.76119615.007230.5858
9637.074235.30129681.493231.49369703.846234.42489726.199233.79359737.376230.0432
9759.729217.41339771.168214.24339794.048212.43029816.928213.17619944.856209.3611
9969.476210.90269992.765203.407410016.08204.846210027.73208.889610053.87212.3202
   10117213.234210131.25218.436110172.37240.682610185.54245.666510211.37247.3832
10261.18247.177510285.47249.873910309.46249.853510321.46251.605910446.99257.5327
#Mann= 3 , 0 , 0
9553.036    0.04       09553.036    0.04       010446.99    0.04       0
#XS Ineff= 2 , 0
       0                               0
Bank Sta=9553.036,10446.99
Exp/Cntr=0.3,0.1

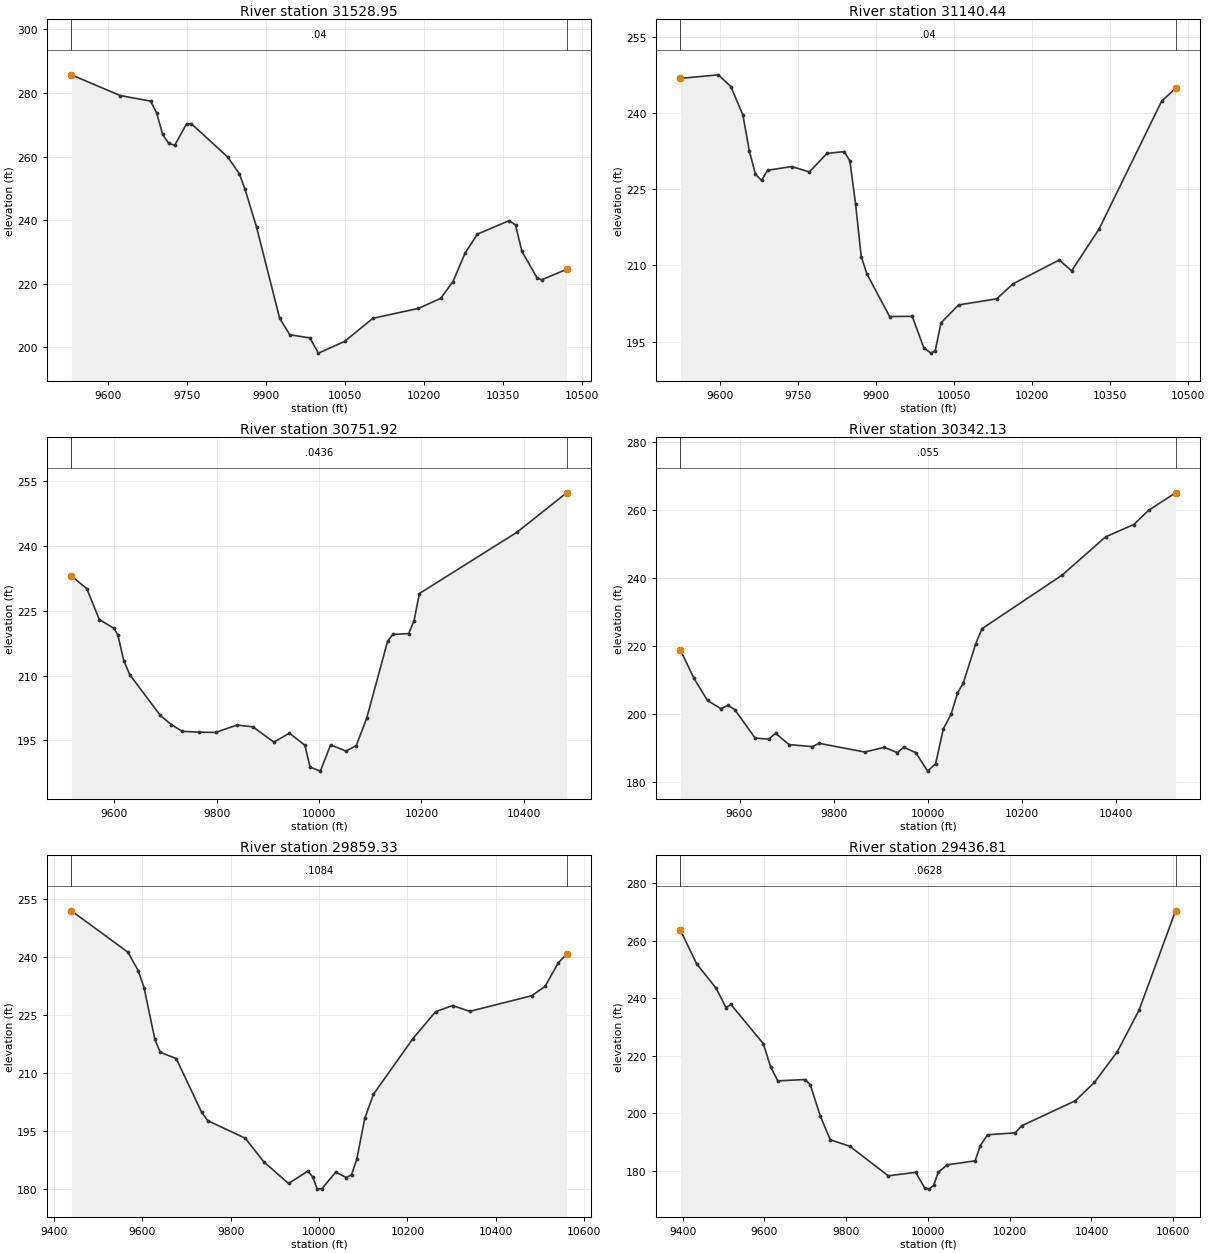
Type RM Length L Ch R = 1 ,31528.95,388.514000,388.514000,388.514000
XS GIS Cut Line= 6
 916724.92731812806922.450670083916548.340712712807024.198848792
916345.279122031807121.555748763 916265.36733036807183.847298004
916058.704839066807297.919734547915917.195148803807398.698020554
#Sta/Elev= 30
9529.755285.7115 9622.75279.17529680.134277.44879691.588  273.739703.041266.9661
 9714.71264.11149725.949263.56199748.524 270.3289757.524270.33469826.539259.8675
9848.481254.65029859.452249.73639881.395237.77989925.357209.05479944.591203.9245
 9982.59202.9374    9999198.146710048.46201.824710102.48209.113410188.98212.2259
10231.05215.372410254.28220.615710277.52229.628810300.92235.594810361.24239.8345
10373.31238.414310385.39230.203310414.17221.828410422.93221.216710470.23224.5178
#Mann= 3 , 0 , 0
9529.755    0.04       09529.755    0.04       010470.23    0.04       0
#XS Ineff= 2 , 0
       0                               0
Bank Sta=9529.755,10470.23
Exp/Cntr=0.3,0.1

Type RM Length L Ch R = 1 ,31140.44,388.514000,388.514000,388.514000
XS GIS Cut Line= 6
916303.725388321806535.811861192 916186.31020509806715.488839751
916067.064750289 806973.96919306916010.405335108 807076.28839781
915931.819159342807183.172099429915798.238606662807334.806338441
#Sta/Elev= 30
9524.298246.83699597.154247.53269621.365245.21219644.441239.59539656.907232.4658
9668.568227.94759680.229226.7419 9691.89228.74299738.533229.46449772.197228.4015
 9805.84232.05749839.124232.40869850.012 230.577  9860.9222.09139871.788 211.735
9882.676208.32799926.227199.92859969.779199.96229991.769193.823910005.65192.7159
10013.91193.172310025.04198.686610058.81202.208110131.95203.410710163.65206.3791
10252.15211.063310276.01208.9306 10328.5217.113610448.98242.339910475.72244.8786
#Mann= 3 , 0 , 0
9524.298    0.04       09524.298    0.04       010475.72    0.04       0
#XS Ineff= 2 , 0
       0                               0
Bank Sta=9524.298,10475.72
Exp/Cntr=0.3,0.1

Type RM Length L Ch R = 1 ,30751.92,409.795900,409.795900,409.795900
XS GIS Cut Line= 6
915907.823367404806340.283002895915771.933070495806581.459542135
915742.503004497806686.570286887915702.035085117806962.642095394
915646.264853957807108.876895863915577.793248833807235.340347367
#Sta/Elev= 30
9516.522232.98689546.604230.08169570.946222.95229599.908220.88419607.146219.3692
9618.814213.46099630.482210.19559690.121200.80439711.931198.63989732.898197.1187
9765.475196.92479797.934196.86049840.046198.56399871.004198.14649911.977194.6252
  9942.3196.69249972.491193.88349982.525188.868210002.59187.919810022.64193.9818
10052.77192.5513 10072.9193.836510093.15200.127810133.88217.908110144.19219.5243
10175.12219.691510185.49222.620510196.04228.953310386.97  243.1410483.49252.2197
#Mann= 3 , 0 , 0
9516.522  0.0436       09516.522  0.0436       010483.49  0.0436       0
#XS Ineff= 2 , 0
       0                               0
Bank Sta=9516.522,10483.49
Exp/Cntr=0.3,0.1

Type RM Length L Ch R = 1 ,30342.13,482.796000,482.796000,482.796000
XS GIS Cut Line= 6
915714.869551174806282.879390855 915388.81540495806622.245043237
915355.523656988806664.641672194915354.401302102806666.297063238
915308.051699392806726.000041716915017.530296942807068.292202905
#Sta/Elev= 30
9474.477218.89479503.157210.55299532.024 203.9999560.623201.58559575.325202.5361
9589.759201.3436 9633.06192.93529661.927192.61999676.361194.34149705.228191.0129
9754.769190.42279768.637191.3977 9865.71188.8344  9907.3190.21079935.047 188.649
9948.597190.25379974.026 188.6479999.433183.205110016.33185.428110032.64195.6796
10048.94199.930610062.66 206.12610075.32209.2681 10101.5220.757210114.62225.1394
10285.13240.945210376.95252.159410436.73255.801210468.76260.027210525.54265.1325
#Mann= 3 , 0 , 0
9474.477   0.055       09474.477   0.055       010525.54   0.055       0
#XS Ineff= 2 , 0
       0                               0
Bank Sta=9474.477,10525.54
Exp/Cntr=0.3,0.1

Type RM Length L Ch R = 1 ,29859.33,422.523800,422.523800,422.523800
XS GIS Cut Line= 6
915659.703713214805948.332397627915357.554219669806151.079441676
915266.090247486806200.699364788915103.017920395806275.487764873
914908.554459005806430.024886883914740.221462003806577.449322868
#Sta/Elev= 30
9439.963251.96739567.737241.25869591.175236.45539604.347232.04879628.753218.6523
9640.957215.33519677.019213.70729734.757199.75979748.407197.61499833.138193.0848
9875.079186.96389931.177181.36069974.741184.54629985.443 183.1219996.146 179.891
10006.92180.049410037.82184.297610061.78182.887510073.64183.660110085.49187.6538
10103.47198.195910123.14 204.45410212.11218.8204 10263.6225.835310302.21227.4391
10340.92225.931610481.52229.993510511.46 232.412 10541.4238.528210560.03240.7192
#Mann= 3 , 0 , 0
9439.963  0.1084       09439.963  0.1084       010560.03  0.1084       0
#XS Ineff= 2 , 0
       0                               0
Bank Sta=9439.963,10560.03
Exp/Cntr=0.3,0.1

Type RM Length L Ch R = 1 ,29436.81,422.523800,422.523800,422.523800
XS GIS Cut Line= 6
915398.108606705805661.836288427915013.085018163  805922.2590349
914815.855482999806020.330367817914732.312647793806073.603538321
914618.613951762806169.347310259914422.845744549806367.119758868
#Sta/Elev= 30
9394.277263.73179433.978252.02369481.942243.43259505.924236.72289517.915237.8385
9597.315224.1548 9614.99216.12369632.501211.23129700.071211.70089712.225209.8281
9736.534198.98739760.843 190.7219808.934188.43929902.805178.16319970.011179.3633
9991.976173.933310002.93173.516910013.86174.8389 10024.8179.311710046.95181.9758
10115.37183.378210127.91188.646210145.67192.446810213.54193.139710229.29195.5774
10360.37204.289710407.19210.7027 10463.3 221.38310516.54235.893710605.72 270.457
#Mann= 3 , 0 , 0
9394.277  0.0628       09394.277  0.0628       010605.72  0.0628       0
#XS Ineff= 2 , 0
       0                               0
Bank Sta=9394.277,10605.72
Exp/Cntr=0.3,0.1

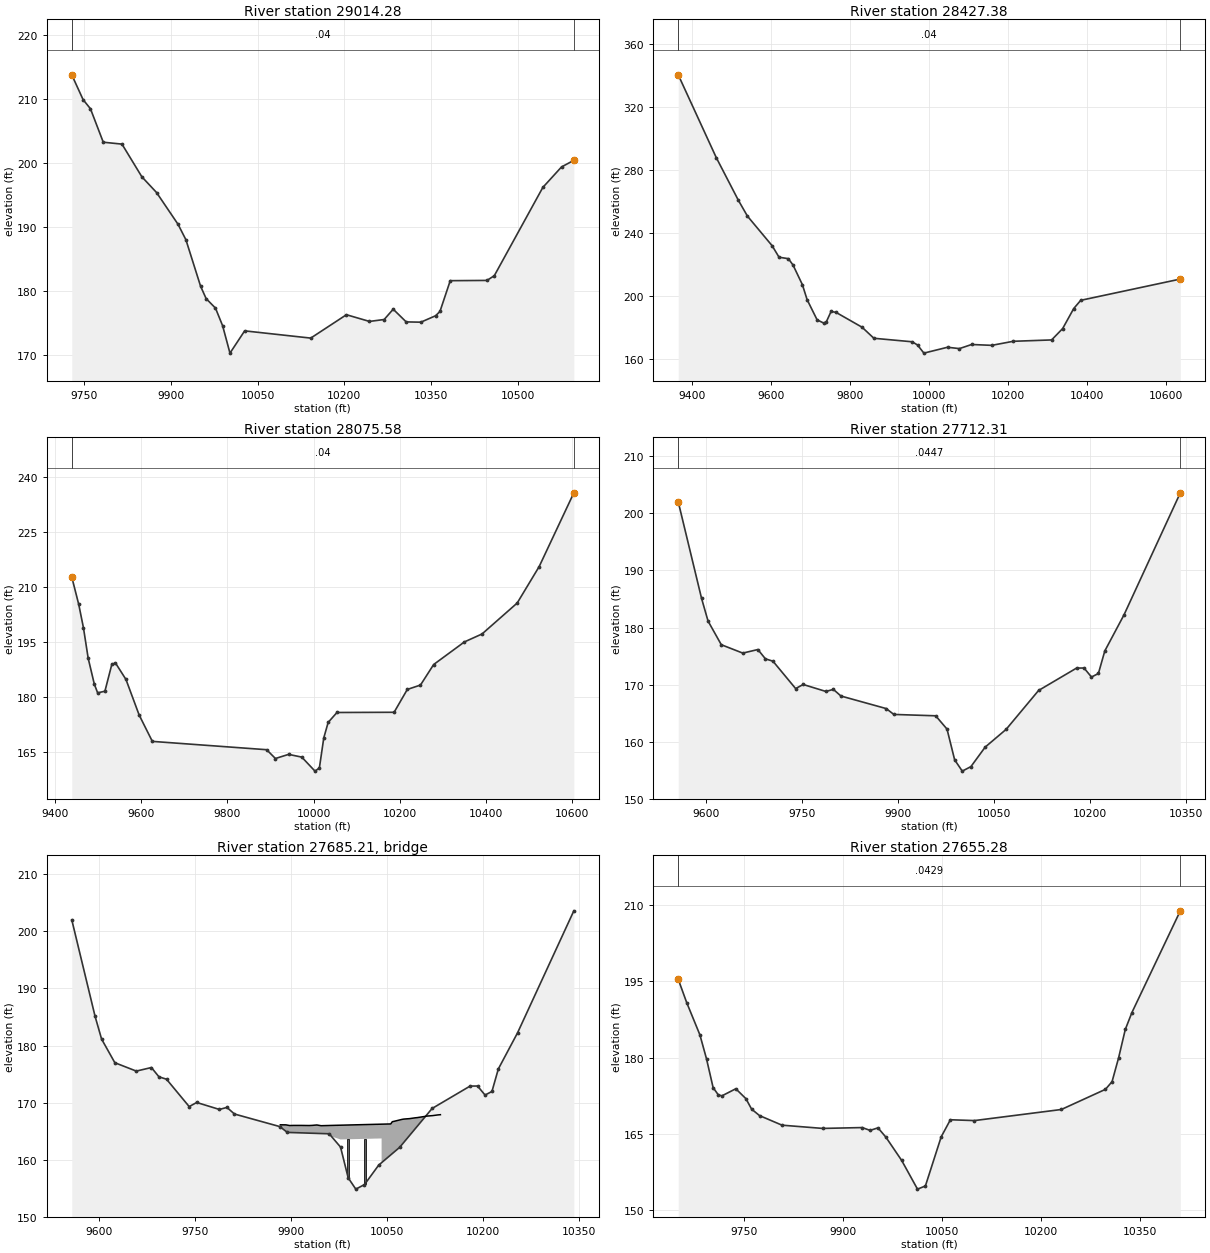
Type RM Length L Ch R = 1 ,29014.28,586.905000,586.905000,586.905000
XS GIS Cut Line= 2
914848.671817081805409.546895382914311.842648934806093.329299501
#Sta/Elev= 30
9728.127 213.7699747.774209.88399760.487208.46579782.655203.23729815.043202.9408
9849.483197.8315 9874.91195.37639912.206190.39919925.764187.99239951.192180.7269
9960.788178.79089976.982 177.3079989.333174.551510002.05170.274410027.47173.7539
 10141.9172.6225 10203.7176.276410243.61175.228310269.03175.528210284.67177.1384
10307.17175.1546 10332.6175.112310358.03176.113610365.64176.784910383.45181.5968
10447.02181.636910459.74182.375510543.77196.172510576.16199.376610597.46200.4041
#Mann= 3 , 0 , 0
9728.127    0.04       09728.127    0.04       010597.46    0.04       0
#XS Ineff= 2 , 0
       0                               0
Bank Sta=9728.127,10597.46
Exp/Cntr=0.3,0.1

Type RM Length L Ch R = 1 ,28427.38,351.800000,351.800000,351.800000
XS GIS Cut Line= 6
914851.448401344805036.215366579914623.171123441805154.420348546
914472.379868889 805258.76978367914403.532055061805323.000133434
 914282.66011297805456.489979039913886.415877537805845.414469394
#Sta/Elev= 30
9364.826340.5684 9460.99288.01029517.114260.78889539.952250.78629602.463231.9648
9619.886224.69119643.501223.75819655.347219.6889 9679.04207.19829690.886197.7262
9716.267184.86619733.353182.80629739.198183.4628 9751.53190.20359763.863189.6698
9830.019180.19639859.834 173.192 9956.68170.96179970.243168.92599986.358163.7521
10046.15  167.4810076.29166.628710107.19169.235510158.09168.696110212.39 171.273
10309.55172.136910337.52179.376310365.49192.079910383.18197.299410635.17 210.811
#Mann= 3 , 0 , 0
9364.826    0.04       09364.826    0.04       010635.17    0.04       0
#XS Ineff= 2 , 0
       09931.268                       0
Bank Sta=9364.826,10635.17
Exp/Cntr=0.3,0.1

Type RM Length L Ch R = 1 ,28075.58,363.265600,363.265600,363.265600
XS GIS Cut Line= 3
914569.760573295 805163.62515355914455.796839275805214.608929296
913436.121324361805415.544986646
#Sta/Elev= 30
9439.405212.67829455.575205.1885 9466.53 198.7979477.485190.49039491.747183.4249
9499.395181.06529516.235181.51169532.261188.82629540.723189.22019565.065184.7199
9595.642175.01159626.219167.82459891.219165.55279911.604163.15299942.181164.2805
9972.758163.531110003.33159.709610013.53160.571510023.72168.776610033.91173.0058
 10054.3175.7082 10186.8175.764810217.37181.992410247.95183.193710278.53188.7992
10349.87194.965610390.64197.129810472.18205.571910523.14215.519810603.54235.6398
#Mann= 3 , 0 , 0
9439.405    0.04       09439.405    0.04       010603.54    0.04       0
#XS Ineff= 2 , 0
       09746.399                       0
Bank Sta=9439.405,10603.54
Exp/Cntr=0.3,0.1

Type RM Length L Ch R = 1 ,27712.31,57.028400,57.028400,57.028400
XS GIS Cut Line= 6
914530.017083143 805135.62561513914452.267684104805156.358788207
914206.925136027805002.587754553914004.776698527804871.277658399
913970.221410066804850.544485322913837.183549489 804843.63342763
#Sta/Elev= 30
9557.194202.02129593.576185.12789603.784181.12749624.483176.98529658.039 175.516
9681.643176.14049693.445 174.5119705.246174.09489740.652169.30179752.454 170.017
9787.859168.80029799.661169.15499811.463167.99589882.274165.79529894.075164.7727
9959.496164.53199977.203162.20599989.127156.820810001.05154.839810014.57155.6315
10036.83 159.04510069.64162.1634 10120.3168.970310179.66172.892410191.32172.9036
10202.99171.320510213.79171.9453 10223.8175.898210253.84182.225310341.78203.5923
#Mann= 3 , 0 , 0
9557.194  0.0447       09557.194  0.0447       010341.78  0.0447       0
#XS Ineff= 2 , 0
       09940.148        10060.19       0
Bank Sta=9557.194,10341.78
Exp/Cntr=0.3,0.1

Type RM Length L Ch R = 3 ,27685.21,,,
BEGIN DESCRIPTION:
END DESCRIPTION:
Bridge Culvert--1,0,-1,-1, 0
Deck Dist Width WeirC Skew NumUp NumDn MinLoCord MaxHiCord MaxSubmerge Is_Ogee
17.359200,22.310000,2.6,0, 27, 27, , , 0.95, 0, 0,0,,
 9883.13 9891.82 9897.64 9903.90 9915.46 9915.98 9928.06 9933.29 9940.14 9946.79
 9962.99 9962.9910041.4010041.4010055.6210058.0810060.9410073.0110075.9110085.09
10093.7310097.1710109.2510111.5610121.3310129.3910133.25
  166.11  166.10  165.98  166.00  166.00  166.00  165.98  166.01  166.08  165.95
  166.00  166.00  166.22  166.22  166.26  166.65  166.72  167.05  167.11  167.19
  167.33  167.37  167.58  167.63  167.72  167.84  167.88
 -833.89 -833.90 -834.02 -834.00 -834.00 -834.00 -834.02 -833.99 -833.92 -834.05
 -834.00  163.50  163.72 -833.78 -833.74 -833.35 -833.28 -832.95 -832.89 -832.81
 -832.67 -832.63 -832.42 -832.37 -832.28 -832.16 -832.12
 9883.13 9891.82 9897.64 9903.90 9915.46 9915.98 9928.06 9933.29 9940.14 9946.79
 9960.86 9960.8610039.2710039.2710055.6210058.0810060.9410073.0110075.9110085.09
10093.7310097.1710109.2510111.5610121.3310129.3910133.25
  166.11  166.10  165.98  166.00  166.00  166.00  165.98  166.01  166.08  165.95
  165.99  165.99  166.21  166.21  166.26  166.65  166.72  167.05  167.11  167.19
  167.33  167.37  167.58  167.63  167.72  167.84  167.88
 -833.89 -833.90 -834.02 -834.00 -834.00 -834.00 -834.02 -833.99 -833.92 -834.05
 -834.01  163.49  163.71 -833.79 -833.74 -833.35 -833.28 -832.95 -832.89 -832.81
 -832.67 -832.63 -832.42 -832.37 -832.28 -832.16 -832.12
Pier Skew, UpSta & Num, DnSta & Num=  ,9988.63, 2 ,9986.50, 2 , 0 , 0 , 0 ,,
    3.00    3.00
 -833.93  166.07
    3.00    3.00
 -833.93  166.07
Pier Skew, UpSta & Num, DnSta & Num=  ,10015.77, 2 ,10013.64, 2 , 0 , 0 , 0 ,,
    3.00    3.00
 -833.85  166.15
    3.00    3.00
 -833.86  166.14
BR Coef=-1 , 0 , 0 ,, 0 ,,,0.8,0,1,0,
WSPro=,,,, 1 ,,,, 0 ,,,, 0 ,,,,-1 ,-1 ,-1 , 0 , 0 , 0 , 0 , 0
BC Design=,, 0 ,, 0 ,,,,,,

Type RM Length L Ch R = 1 ,27655.28,369.761000,369.761000,369.761000
XS GIS Cut Line= 5
914467.778486849805070.574865918914407.235555963805068.016713909
914061.885034709804841.193902419913945.062759618804758.480320785
913801.806247098804767.007494149
#Sta/Elev= 30
9650.783195.40379663.573190.8203 9683.59184.46599693.599179.74779703.608174.0854
 9711.38172.67399716.875172.45859737.982173.85699753.307171.9057 9761.91169.8511
9773.874168.57989807.954166.69289869.586166.05389929.406166.2218 9941.37165.6671
9953.334166.16689965.298164.33249989.226 159.74910013.15154.108410025.12154.7283
10049.05164.401310062.98167.757610099.41167.596310231.02169.777310297.81173.7439
10307.83 175.25310317.85 179.99410327.87185.522510337.88188.849110411.21  208.87
#Mann= 3 , 0 , 0
9650.783  0.0429       09650.783  0.0429       010411.21  0.0429       0
#XS Ineff= 2 , 0
       09941.902        10058.21       0
Bank Sta=9650.783,10411.21
Exp/Cntr=0.3,0.1

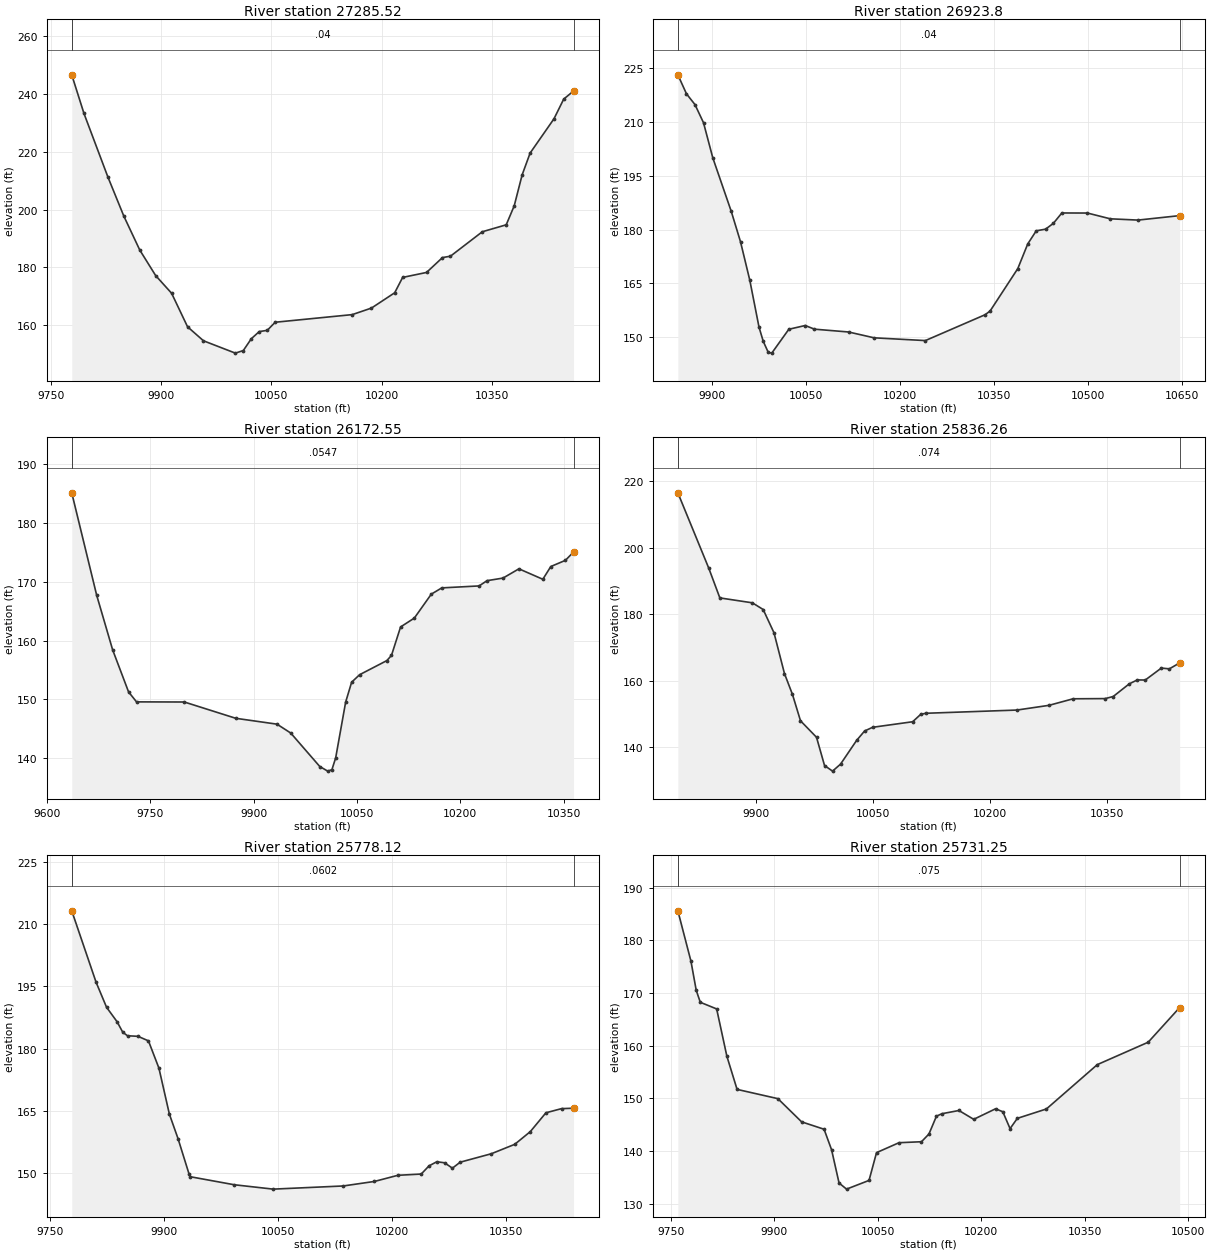
Type RM Length L Ch R = 1 ,27285.52,361.725800,361.725800,361.725800
XS GIS Cut Line= 2
914270.349073019804499.111970598 913640.53052462804760.086507227
#Sta/Elev= 30
9778.699246.58479795.314233.21039827.788211.25849849.437197.73239871.086186.0014
9892.735177.14649914.384171.03869936.033159.44459957.682154.601910000.98150.3354
 10011.8151.230510022.63155.302210033.45157.789510044.28158.2086 10055.1161.0168
 10159.8163.654510185.93165.919210217.47171.204910228.29176.520810260.77178.2402
10282.42183.383510293.24 183.85710336.54192.312210369.01194.713810379.84201.2433
10390.66211.988110401.49219.529110433.96231.399810447.16238.197410460.45240.9741
#Mann= 3 , 0 , 0
9778.699    0.04       09778.699    0.04       010460.45    0.04       0
#XS Ineff= 2 , 0
       0                10127.97       0
Bank Sta=9778.699,10460.45
Exp/Cntr=0.3,0.1

Type RM Length L Ch R = 1 , 26923.8,751.243500,751.243500,751.243500
XS GIS Cut Line= 2
914065.049104204804137.227279805913476.986481666804680.054315994
#Sta/Elev= 30
9845.896223.23269859.572217.94489873.181214.9257 9886.79209.85919901.585200.0802
9931.071 185.1049945.814176.63029960.557165.95249975.301152.82219982.053148.8607
9990.044145.76949995.663 145.55310022.88152.213610049.02153.264310063.71152.2392
10118.14151.454710158.97149.822810240.68 149.05610335.89156.268510343.88 157.304
10388.11169.158910403.94176.032610417.54179.698410432.34180.150410444.76181.7698
10458.37184.6742 10499.2 184.65310535.54183.044710579.77182.6867 10646.2 183.932
#Mann= 3 , 0 , 0
9845.896    0.04       09845.896    0.04       0 10646.2    0.04       0
#XS Ineff= 2 , 0
       0                10135.05       0
Bank Sta=9845.896,10646.2
Exp/Cntr=0.3,0.1

Type RM Length L Ch R = 1 ,26172.55,336.289300,336.289300,336.289300
XS GIS Cut Line= 2
913654.449166574803973.683236851913289.084815293804603.501785249
#Sta/Elev= 30
9636.043185.16159672.248167.69779695.369158.41449718.491151.24319730.052149.5473
9799.417149.52419874.089146.74749933.875145.74999953.804144.24049995.951138.5359
10007.51137.748310013.59137.994610019.07140.027610033.52149.514510042.19152.8975
10053.76154.1725 10093.3156.5806   10100157.463810113.23162.312410133.16163.8201
 10157.8167.900910173.02168.965710227.17169.300310238.73170.197810261.85170.6362
10284.97172.213410319.65170.433710331.22172.606410352.38173.656310364.17175.0716
#Mann= 3 , 0 , 0
9636.043  0.0547       09636.043  0.0547       010364.17  0.0547       0
#XS Ineff= 2 , 0
       0                               0
Bank Sta=9636.043,10364.17
Exp/Cntr=0.3,0.1

Type RM Length L Ch R = 1 ,25836.26,58.139200,58.139200,58.139200
XS GIS Cut Line= 4
913372.596667014803876.252743176913278.645833828803973.683236851
913236.889907967804151.145921758913160.337377222804467.795026202
#Sta/Elev= 30
9799.816216.57789839.573193.82699853.644 184.9619895.319 183.4829909.211181.4692
9923.103174.45349936.518162.19769946.792155.90169957.065147.98929977.611143.0276
9987.884134.53259998.157132.840110008.43134.947610028.98142.067410039.25144.9132
10049.52146.028210100.89147.698510111.16149.906110117.47150.244310234.61151.2165
10275.76152.638410306.63154.604910347.78154.663510358.07155.293710378.64159.0959
10388.93160.281310399.22160.252610419.79163.848910430.08163.614410443.25165.3972
#Mann= 3 , 0 , 0
9799.816   0.074       09799.816   0.074       010443.25   0.074       0
#XS Ineff= 2 , 0
       0                               0
Bank Sta=9799.816,10443.25
Exp/Cntr=0.3,0.1

Type RM Length L Ch R = 1 ,25778.12,46.871300,46.871300,46.871300
XS GIS Cut Line= 4
913348.239043596803858.854440734913216.011945037803984.122218316
913191.654321618804095.471353944913111.622130385 804450.39672376
#Sta/Elev= 30
9778.584213.23939810.595195.9976 9824.37189.95259838.145186.47829845.681183.9317
 9851.92183.07919865.695182.9441 9879.47 181.8479893.245 175.258 9907.02164.1401
9918.382158.24079932.922149.6701 9934.57149.04299992.334147.109510043.52146.0535
10135.73146.817310176.74147.909910207.49149.390610238.24149.692310248.49151.6675
10258.74152.6642   10269152.411210279.25 151.112 10289.5152.5581 10330.5154.5985
10361.26156.869410381.76159.942510402.26164.482510422.76165.485210438.55165.5855
#Mann= 3 , 0 , 0
9778.584  0.0602       09778.584  0.0602       010438.55  0.0602       0
#XS Ineff= 2 , 0
       0                               0
Bank Sta=9778.584,10438.55
Exp/Cntr=0.3,0.1

Type RM Length L Ch R = 1 ,25731.25,388.380200,388.380200,388.380200
XS GIS Cut Line= 4
913303.003457246803831.017156827 913188.17466113803956.284934409
913090.744167455804185.942526642 912993.31367378804478.234007667
#Sta/Elev= 30
9760.104185.61399779.073176.05579786.747170.51319792.638168.25429816.345166.9932
9831.144158.02259845.943151.72369905.139149.96429939.505145.56399972.093144.1596
9982.956140.26819993.819133.954710004.68132.793910037.27134.449110048.13139.7178
10080.72141.604110113.31141.788810124.17143.257710135.03146.644110143.01147.1085
10167.62147.718410189.06146.042910220.68148.038810231.22147.484710241.76144.2763
 10252.3146.226310294.47148.009210368.25156.423710442.04160.677310487.61167.2537
#Mann= 3 , 0 , 0
9760.104   0.075       09760.104   0.075       010487.61   0.075       0
#XS Ineff= 2 , 0
       0                               0
Bank Sta=9760.104,10487.61
Exp/Cntr=0.3,0.1