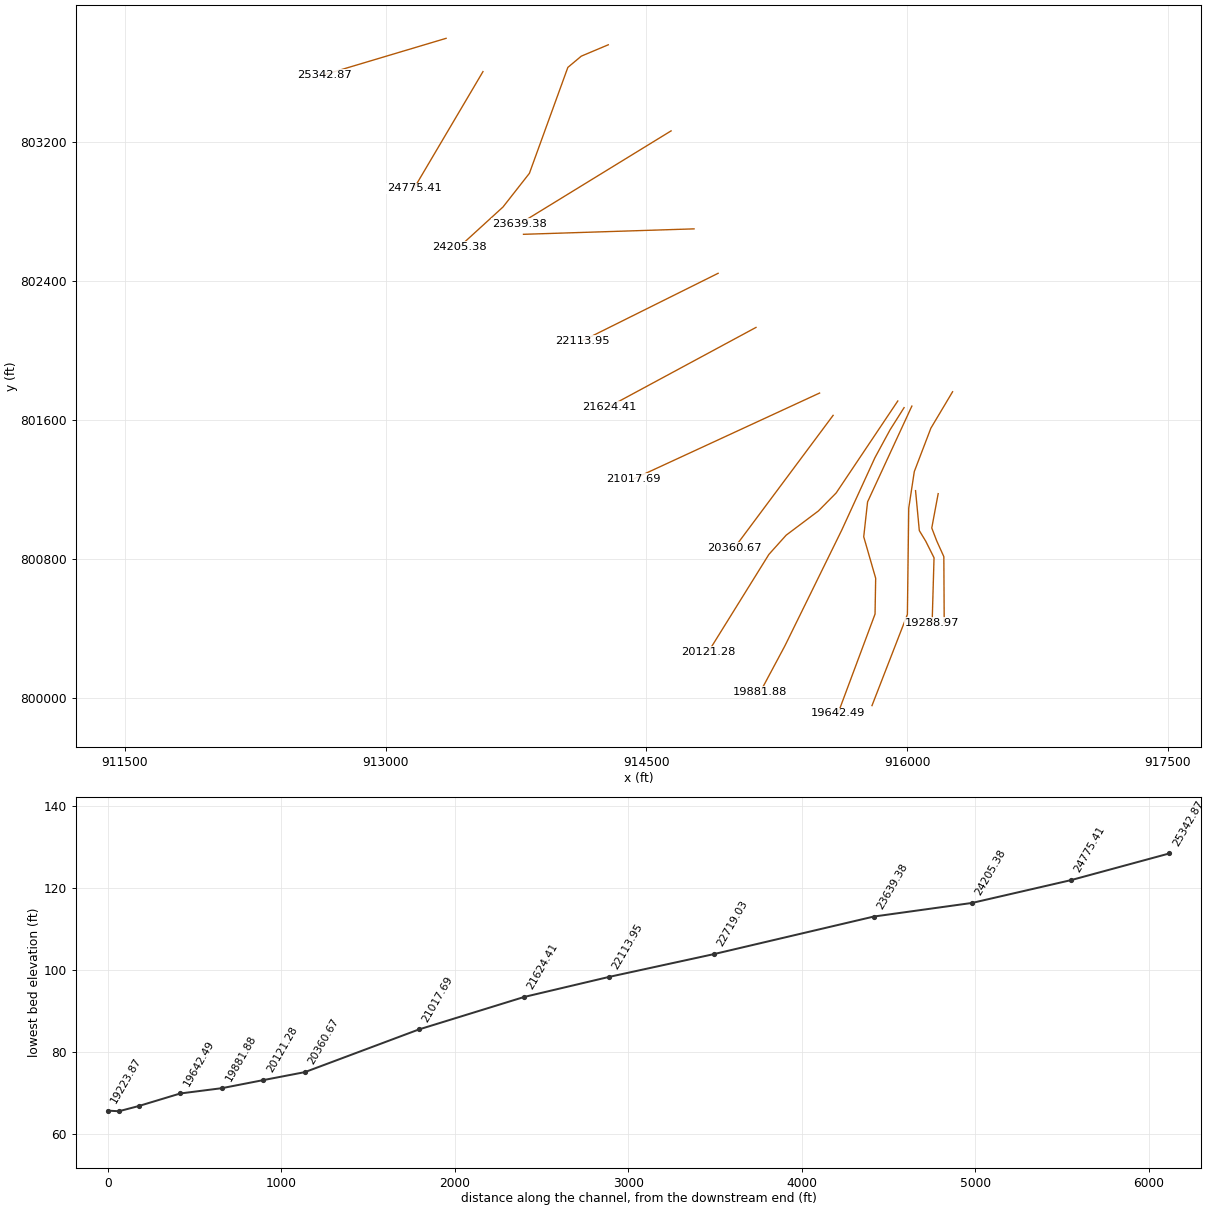
HEC-RAS study 13252_ras.prj: 13252

--- 13252_ras.g01 (geometry) --- (continued)

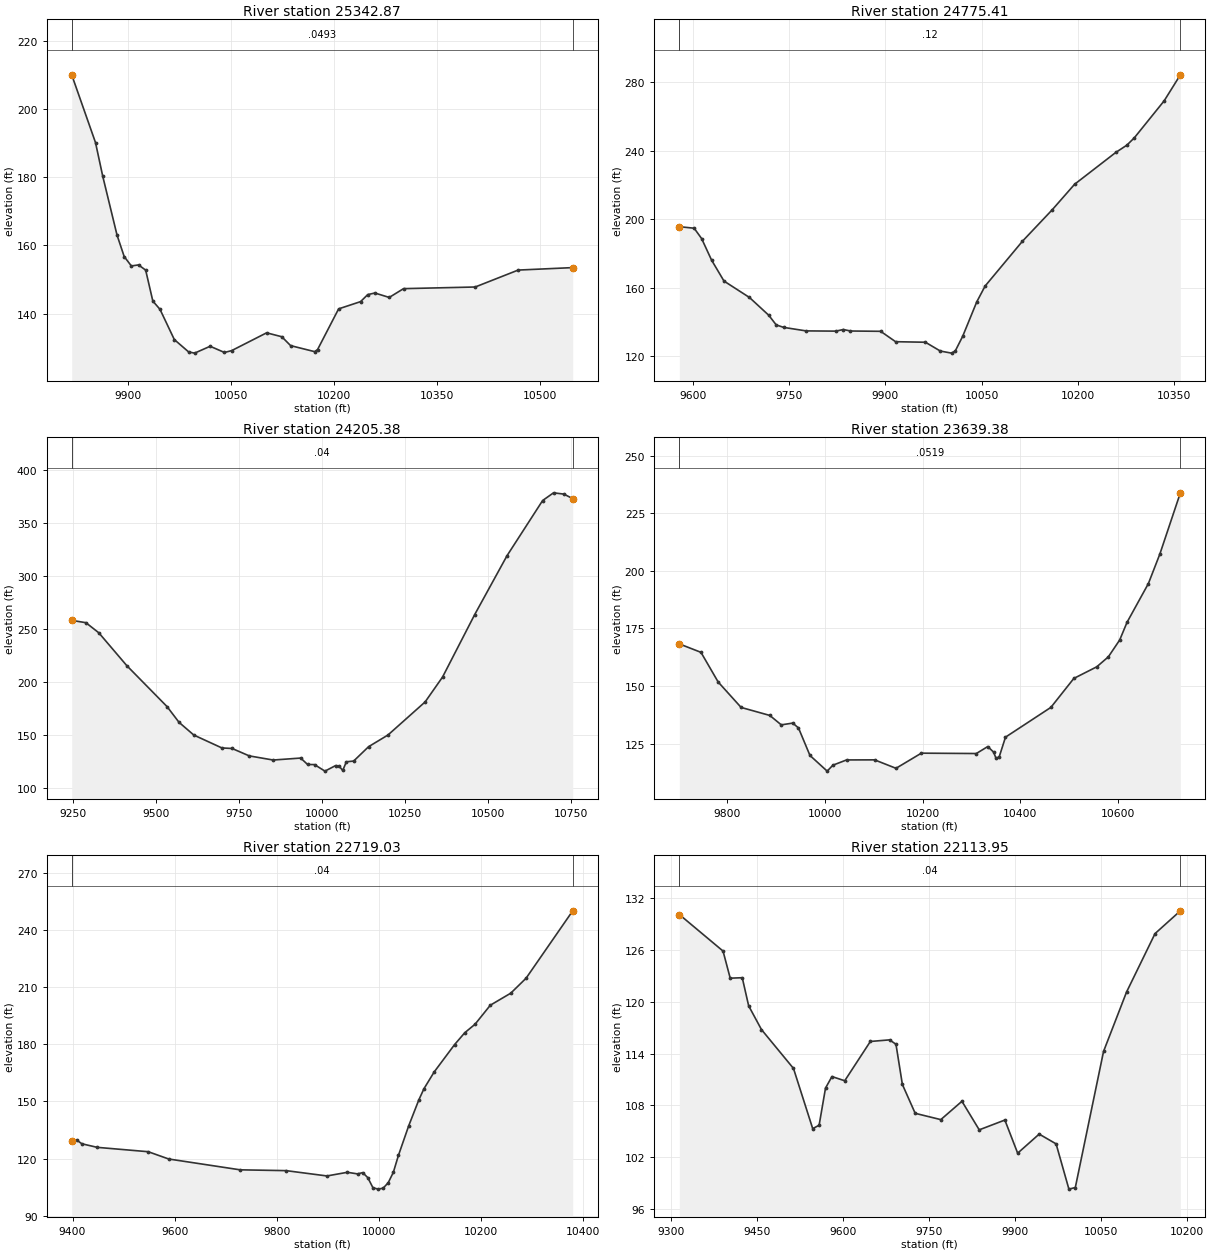
Type RM Length L Ch R = 1 ,25342.87,567.462100,567.462100,567.462100
XS GIS Cut Line= 2
913348.239043596803796.220551943912648.827285429803587.440922639
#Sta/Elev= 30
 9817.65210.07569852.339190.17199862.775180.38019883.647163.05629894.083156.7546
9904.519153.98239914.955154.29299925.391152.76319935.827143.67959946.263141.2538
9967.135132.38189988.007128.75279996.721128.403710019.32130.416110040.19128.5948
10050.62129.1359 10101.6 134.36310123.68133.214610136.56 130.60510171.52128.8417
10175.86129.464810206.49141.390110238.47143.518110248.91145.574710259.34146.0467
10280.22144.746410301.09147.325610405.45147.808810468.06152.775810547.56153.5006
#Mann= 3 , 0 , 0
 9817.65  0.0493       0 9817.65  0.0493       010547.56  0.0493       0
#XS Ineff= 2 , 0
       0                               0
Bank Sta=9817.65,10547.56
Exp/Cntr=0.3,0.1

Type RM Length L Ch R = 1 ,24775.41,570.028900,570.028900,570.028900
XS GIS Cut Line= 2
913560.498333387803604.839225081913163.817037711802933.264750822
#Sta/Elev= 30
9579.261195.73099602.303194.84179613.917188.79989629.397176.23369648.759163.9789
9688.385154.39889718.444144.01769730.059138.37849741.673136.92299776.515134.8792
9822.972134.74149834.586135.68279845.686134.81479892.657 134.6369915.886128.5695
9962.343128.25429985.571123.108610002.99 121.896 10008.8 123.15910020.41131.7761
10042.31151.864310055.26 161.07310113.33187.212210159.78205.621110194.63220.5218
 10258.6239.063510275.93243.341410287.54247.6189   10334269.228510359.24284.4174
#Mann= 3 , 0 , 0
9579.261    0.12       09579.261    0.12       010359.24    0.12       0
#XS Ineff= 2 , 0
       0                               0
Bank Sta=9579.261,10359.24
Exp/Cntr=0.3,0.1

Type RM Length L Ch R = 1 ,24205.38,566.004300,566.004300,566.004300
XS GIS Cut Line= 6
914281.422610025803759.128115276914126.320287964803693.844407889
914048.784096428803629.101936462913827.530248638 803019.57181195
913675.575709769 802825.81727348913425.729834722802597.804868442
#Sta/Elev= 30
9246.094258.2802 9288.81256.10019327.655246.57449412.032215.60039533.227177.0228
9569.049162.30229613.508150.31889698.024138.17969728.903137.66389780.334130.6938
9852.337126.79629935.142128.65249955.975122.59939976.807122.491210008.14116.3454
10040.07121.532210050.83121.050910061.73116.966510072.63125.144910094.58 125.824
10139.55139.361210197.83150.337510309.73 181.517 10362.1204.904910458.99263.8073
10556.17319.182310663.36371.1281 10696.1378.365510727.17377.174310753.88 372.916
#Mann= 3 , 0 , 0
9246.094    0.04       09246.094    0.04       010753.88    0.04       0
#XS Ineff= 2 , 0
       0                               0
Bank Sta=9246.094,10753.88
Exp/Cntr=0.3,0.1

Type RM Length L Ch R = 1 ,23639.38,920.344900,920.344900,920.344900
XS GIS Cut Line= 2
914642.672745277803263.832497219913769.277962691802727.964782007
#Sta/Elev= 30
9702.417168.29239746.615164.63499781.812151.74519828.741140.70059887.402137.2233
9910.866133.1311 9934.33133.89789946.062  131.799969.527119.843110004.72113.0296
10016.46115.609210044.38117.890510101.74117.925710145.51114.255510197.35120.8331
10309.76120.674410333.22123.705710344.96121.308910350.33118.520910356.69119.2989
10369.45127.785210462.28140.721610509.21153.297910556.14158.349110579.79162.6715
10603.06170.015910618.04177.681410661.72194.523710685.19207.3538 10727.1233.9285
#Mann= 3 , 0 , 0
9702.417  0.0519       09702.417  0.0519       0 10727.1  0.0519       0
#XS Ineff= 2 , 0
       0                               0
Bank Sta=9702.417,10727.1
Exp/Cntr=0.3,0.1

Type RM Length L Ch R = 1 ,22719.03,605.080600,605.080600,605.080600
XS GIS Cut Line= 2
914774.899843836  802700.1274981 913793.63558611802668.810553704
#Sta/Elev= 30
  9398.4129.34519408.305129.6882 9418.31127.75159448.325125.87539548.376123.5728
9588.397119.74959728.468114.04599818.514 113.6259898.555110.82449938.575112.7498
9958.585111.9036 9968.59112.57799978.595109.9335  9988.6104.65299998.605103.8949
10008.61104.387410018.62107.260610028.62112.723810038.63121.642410058.64137.1265
10078.65150.874110088.65156.723510108.66165.535110148.68179.941210168.69 186.195
 10188.7190.629110218.72 200.66110258.74206.985410288.75214.851310380.16250.3054
#Mann= 3 , 0 , 0
  9398.4    0.04       0  9398.4    0.04       010380.16    0.04       0
#XS Ineff= 2 , 0
       0                               0
Bank Sta=9398.4,10380.16
Exp/Cntr=0.3,0.1

Type RM Length L Ch R = 1 ,22113.95,489.540700,489.540700,489.540700
XS GIS Cut Line= 2
914913.204323308802444.499025882914130.984020824802055.334696288
#Sta/Elev= 30
9314.803130.05319390.982125.83289403.479122.7027 9424.49122.75579435.659119.5062
9457.997116.76589513.844112.27299547.351105.32259558.521105.7167 9569.69110.0073
9580.859111.33689603.198 110.8549647.874115.39189681.382115.57649692.551115.0682
9703.721110.42569726.059107.09199770.736106.36439807.582108.48199837.751105.1827
9882.428 106.3159904.767102.48739942.283104.69139971.782103.56239994.12198.33499
10005.2998.5207510054.53114.242610094.64121.100810144.33127.853410188.48130.4818
#Mann= 3 , 0 , 0
9314.803    0.04       09314.803    0.04       010188.48    0.04       0
#XS Ineff= 2 , 0
       09674.892                       0
Bank Sta=9314.803,10188.48
Exp/Cntr=0.3,0.1

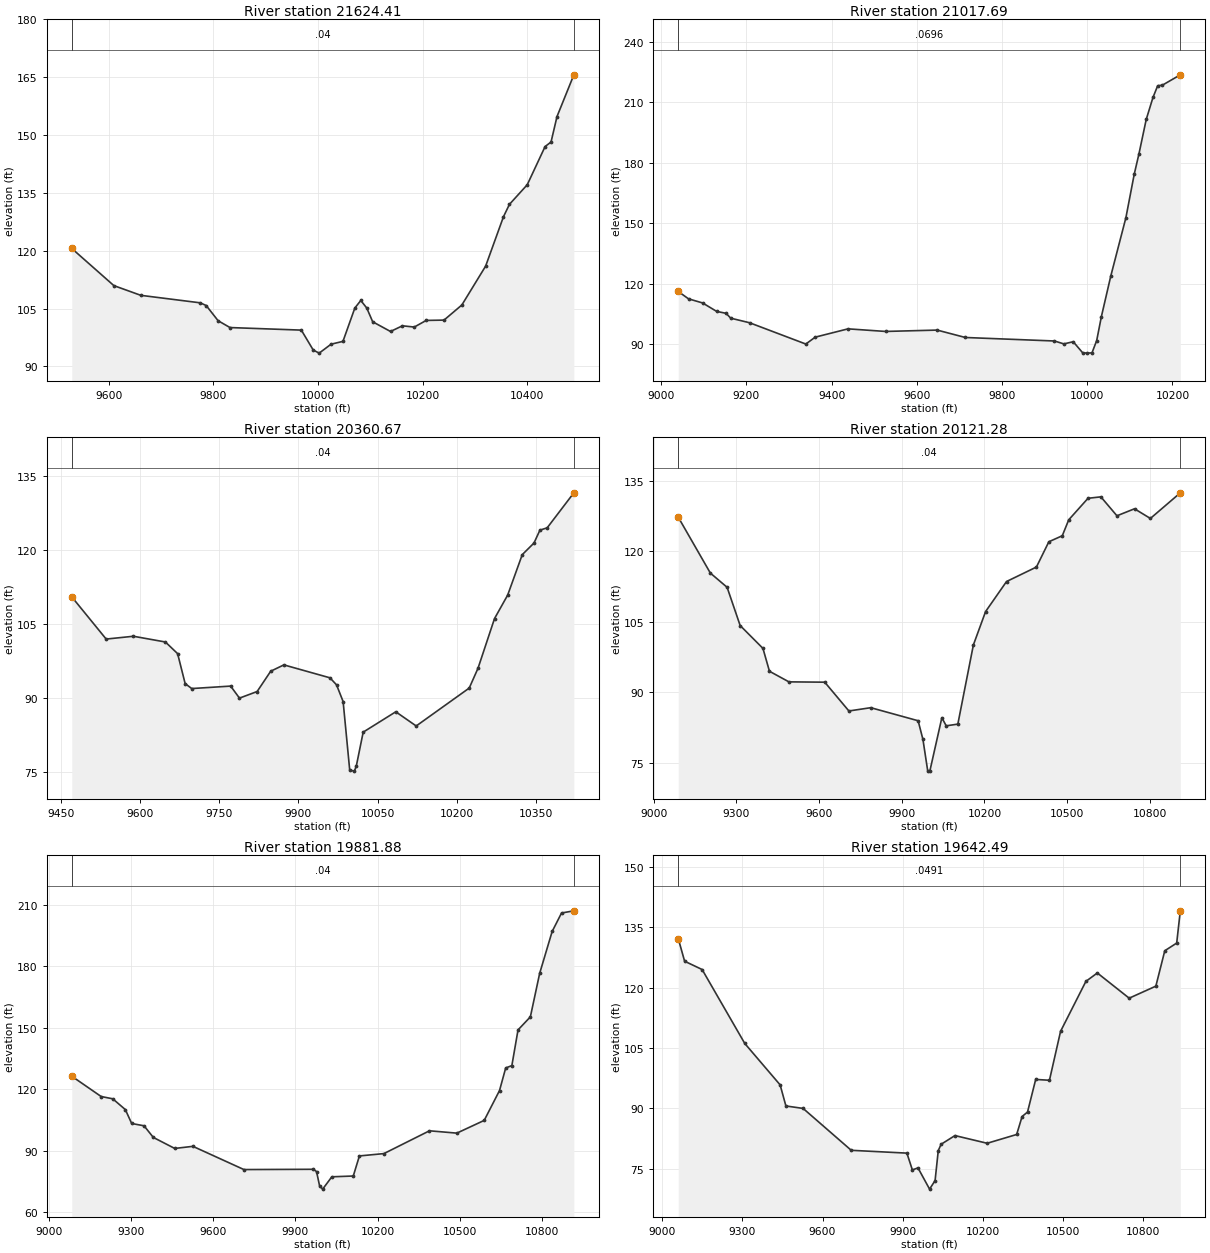
Type RM Length L Ch R = 1 ,21624.41,606.718800,606.718800,606.718800
XS GIS Cut Line= 2
915131.136347881802133.167562207914286.649752662801677.845296582
#Sta/Elev= 30
9529.579120.59429610.003110.95699661.521108.4359 9775.13106.49169786.491105.7874
9809.213101.85319831.935100.08039968.26699.414979990.98894.2504510002.3593.44826
10025.0795.7636410047.7996.4976910070.51105.149410081.87107.099310093.24105.1559
 10104.6101.577310138.6899.06123 10161.4100.534310184.12100.209110206.85 101.929
10240.93 102.01310275.01105.934610320.45116.018310354.54128.8251 10365.9132.0245
10399.98137.120510434.06147.021910445.42 148.19610456.79154.788110488.99165.6174
#Mann= 3 , 0 , 0
9529.579    0.04       09529.579    0.04       010488.99    0.04       0
#XS Ineff= 2 , 0
       09945.627        10078.36       0
Bank Sta=9529.579,10488.99
Exp/Cntr=0.3,0.1

Type RM Length L Ch R = 1 ,21017.69,657.021300,657.021300,657.021300
XS GIS Cut Line= 2
915496.950817699801755.678162501914426.748911316801261.439463916
#Sta/Elev= 30
9039.774116.10789063.953112.45659096.998110.41659130.042106.21739152.072105.2833
9163.087102.86179207.146100.60949339.32590.040279361.35593.454879438.45997.57346
9526.57896.288179647.74296.959169713.83193.290119923.11491.553679945.14390.11512
9967.17391.184699989.203 85.740510000.2285.5352610011.23  85.67410022.2591.75935
10033.26103.626110055.29123.715710090.84152.694810110.37174.223110121.38184.2398
10138.54201.389410154.43212.334810165.44218.113210176.46218.411610218.59223.5388
#Mann= 3 , 0 , 0
9039.774  0.0696       09039.774  0.0696       010218.59  0.0696       0
#XS Ineff= 2 , 0
       09533.375                       0
Bank Sta=9039.774,10218.59
Exp/Cntr=0.3,0.1

Type RM Length L Ch R = 1 ,20360.67,239.393500,239.393500,239.393500
XS GIS Cut Line= 2
915574.783683618801627.253933735915006.603762411800864.491847731
#Sta/Elev= 30
9470.633110.50129535.791 101.937 9587.45102.50639648.016101.34329671.14998.97831
9685.42492.904029697.89491.896439771.58892.396359788.328 89.95569821.80791.29499
9847.52795.417439872.46696.697529959.75294.075069972.22292.648069984.69189.25535
9997.16175.3603210005.9575.1439810009.6376.1542710022.6883.0522910084.4587.18426
10123.1284.3046210223.5691.99478 10240.396.0384310271.49106.096810296.43110.8648
   10324119.059110346.31121.430310357.48124.035710371.24124.506310421.76131.6071
#Mann= 3 , 0 , 0
9470.633    0.04       09470.633    0.04       010421.76    0.04       0
#XS Ineff= 2 , 0
       09885.641                       0
Bank Sta=9470.633,10421.76
Exp/Cntr=0.3,0.1

Type RM Length L Ch R = 1 ,20121.28,239.393600,239.393600,239.393600
XS GIS Cut Line= 6
915946.799421742801709.879259171915592.275672496801180.743977203
915490.193476907801077.433244119915304.840245069800938.049822243
915205.460963873800827.515036623914858.155113933800268.665145297
#Sta/Elev= 30
9089.139127.2102 9205.74115.31219266.445112.29319313.785104.16349396.49299.30319
9420.12394.438149490.78192.184169620.71192.116349708.35885.99348 9787.7186.69161
9959.54483.915919977.01379.947579994.48273.2027810002.1473.2351410045.6684.56264
10061.4182.8379210103.6483.1963710160.03100.030210204.33107.131710280.32113.5191
10388.82116.600310433.85121.973810482.65123.257810505.98126.637810575.96131.2199
10622.62131.524710680.94127.497210744.69128.988610802.29126.932210910.87132.3812
#Mann= 3 , 0 , 0
9089.139    0.04       09089.139    0.04       010910.87    0.04       0
#XS Ineff= 2 , 0
       09905.836                       0
Bank Sta=9089.139,10910.87
Exp/Cntr=0.3,0.1

Type RM Length L Ch R = 1 ,19881.88,239.393600,239.393600,239.393600
XS GIS Cut Line= 6
915983.025813023801671.546047347915902.571199144801544.472779345
915815.065361397801383.196122761915625.487498386800969.360574013
915297.947837091800302.323939896915155.450441294800035.630834257
#Sta/Elev= 30
9082.653126.28989190.007116.39659232.456115.27899278.538110.00199301.535  103.24
 9346.74102.11849380.64496.44691  9458.991.07165 9525.3792.098889711.77880.77178
9965.95680.905319977.11579.780049988.27572.814349999.43171.23273   1003377.24182
10111.3777.6262110133.7687.42061 10223.288.5566810389.8299.6775910489.7998.53742
10589.76104.745410645.75119.3109 10668.3130.309910690.84131.473110713.39148.8782
10758.48155.239310792.38176.414510838.08196.878210872.36205.882510917.35206.9455
#Mann= 3 , 0 , 0
9082.653    0.04       09082.653    0.04       010917.35    0.04       0
#XS Ineff= 2 , 0
       09857.574         10186.1       0
Bank Sta=9082.653,10917.35
Exp/Cntr=0.3,0.1

Type RM Length L Ch R = 1 ,19642.49,239.393500,239.393500,239.393500
XS GIS Cut Line= 6
916027.789562105801680.571200808915773.029443412801129.550395404
915750.873215477800928.808944815915819.660279595800690.064084133
915815.979096106800484.121149335915602.956076451799912.828797299
#Sta/Elev= 30
9059.378132.25489083.257 126.6119148.866124.54529308.721106.15629441.22895.85799
9462.79990.621679527.29890.009129707.66979.594449916.147  78.8979936.62774.72518
9957.71375.2222210001.1669.94407 10021.872.0694810033.7279.5300510044.4181.09787
10096.2883.2584610216.9981.3448410327.4783.5304910347.8187.9985410368.1589.10835
10398.75  97.21510450.3197.0106910491.97109.1742 10586.8 121.59110629.72123.6868
10749.05117.419610848.98120.407510882.45 129.21110927.07131.119110940.65139.1371
#Mann= 3 , 0 , 0
9059.378  0.0491       09059.378  0.0491       010940.65  0.0491       0
#XS Ineff= 2 , 0
       09811.142        10100.15       0
Bank Sta=9059.378,10940.65
Exp/Cntr=0.3,0.1

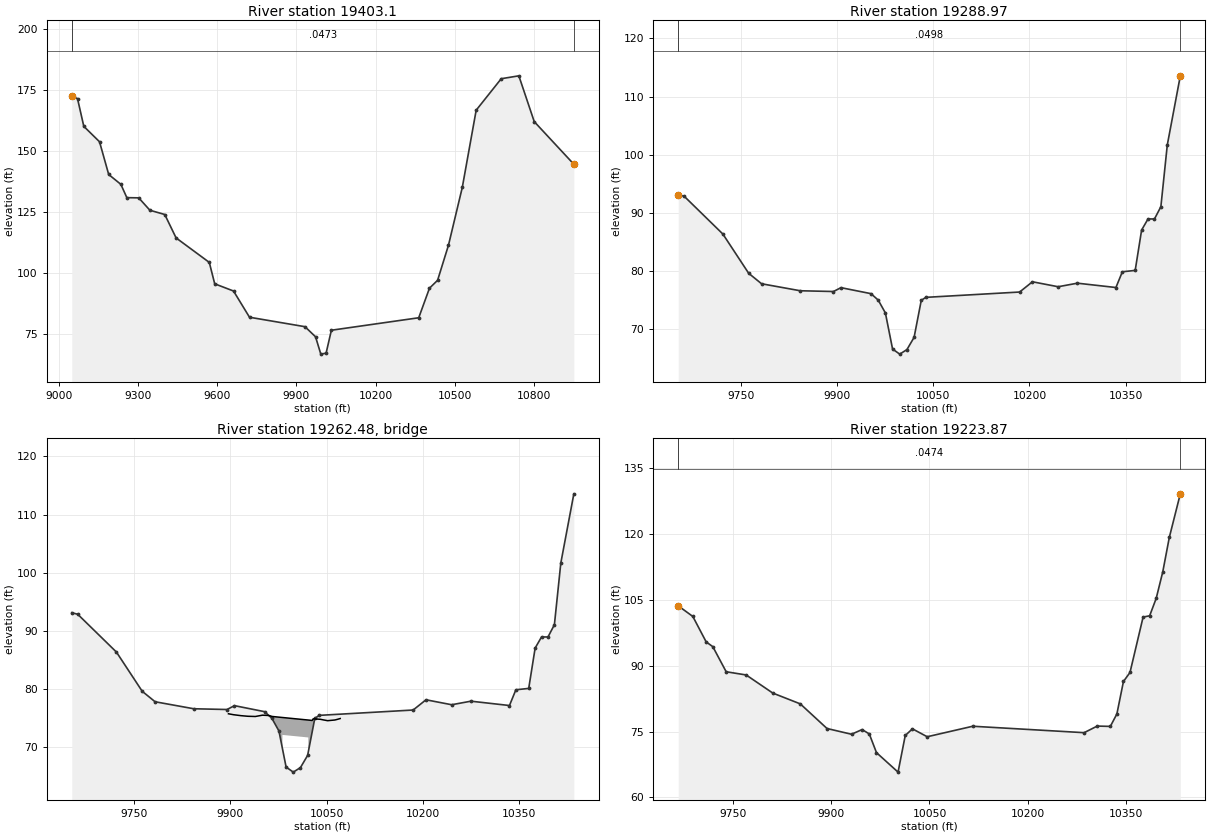
Type RM Length L Ch R = 1 , 19403.1,114.131400,114.131400,114.131400
XS GIS Cut Line= 6
916262.155915748801763.160126107916137.238919899801553.654612579
916041.858452057801304.022049426 916009.83471307801093.347404124
 916002.09762364800482.185663071915798.435822118 799957.45706279
#Sta/Elev= 30
9048.764172.33299070.486171.36479094.408160.0115 9153.92 153.7169188.713140.3316
9234.787136.3037 9257.41130.86429302.443130.78249344.847125.70799401.149123.9755
9444.062114.4025 9569.83104.39319590.39895.635489661.69792.688389722.20981.96785
9932.40378.103119972.43373.979419992.44766.8857910012.4667.2866710032.4876.65563
10363.4681.7558910404.1693.8468710434.9497.0771610476.19111.431610528.51135.0448
10581.14166.623110676.02179.491910742.81180.675110801.09161.9538 10951.2144.5167
#Mann= 3 , 0 , 0
9048.764  0.0473       09048.764  0.0473       0 10951.2  0.0473       0
#XS Ineff= 2 , 0
       09867.261        10198.76       0
Bank Sta=9048.764,10951.2
Exp/Cntr=0.3,0.1

Type RM Length L Ch R = 1 ,19288.97,65.093700,65.093700,65.093700
XS GIS Cut Line= 5
 916048.99942148 801194.26670557916070.700810369800964.231983348
 916107.59317148800903.468094459916155.336227035800807.981983348
916144.485532591800434.718094459
#Sta/Elev= 30
9652.72393.083839662.03192.812159722.29786.304199762.47579.547199782.56377.74129
 9842.8376.535769894.57976.405619906.27877.069429953.07376.036529964.33374.92427
9975.51372.709559986.69466.491389997.87465.6183510009.0566.3995710020.2368.50473
10031.4174.8859910038.5175.3993910184.6676.3169210204.66 78.082310244.6877.22834
10274.6977.8401510334.7277.0933810344.7279.8046610364.7380.0421210374.7486.99343
10384.7488.9121410394.7488.9003810404.7591.0148710414.75101.648910435.04 113.564
#Mann= 3 , 0 , 0
9652.723  0.0498       09652.723  0.0498       010435.04  0.0498       0
#XS Ineff= 2 , 0
       09848.699        10217.37       0
Bank Sta=9652.723,10435.04
Exp/Cntr=0.3,0.1

Type RM Length L Ch R = 3 ,19262.48,,,
BEGIN DESCRIPTION:
END DESCRIPTION:
Bridge Culvert--1,0,-1,-1, 0
Deck Dist Width WeirC Skew NumUp NumDn MinLoCord MaxHiCord MaxSubmerge Is_Ogee
19.421850,26.250000,2.6,0, 23, 23, , , 0.95, 0, 0,0,,
 9896.88 9904.74 9915.48 9916.03 9927.31 9937.07 9938.59 9949.88 9958.66 9961.16
 9964.79 9980.96 9980.9610021.3110021.3110027.2610028.8610040.1410045.0310051.42
10062.7110066.6210070.96
   75.67   75.51   75.36   75.35   75.24   75.21   75.20   75.43   75.38   75.34
   75.21   75.03   75.03   74.59   74.59   74.52   74.80   74.72   74.61   74.48
   74.60   74.71   74.85
 -924.33 -924.49 -924.64 -924.65 -924.76 -924.79 -924.80 -924.57 -924.62 -924.66
 -924.79 -924.97   72.03   71.59 -925.41 -925.48 -925.20 -925.28 -925.39 -925.52
 -925.40 -925.29 -925.15
 9896.88 9904.74 9915.48 9916.03 9927.31 9937.07 9938.59 9949.88 9958.66 9961.16
 9964.79 9968.69 9968.6910009.0410009.0410027.2610028.8610040.1410045.0310051.42
10062.7110066.6210070.96
   75.67   75.51   75.36   75.35   75.24   75.21   75.20   75.43   75.38   75.34
   75.21   75.17   75.17   74.72   74.72   74.52   74.80   74.72   74.61   74.48
   74.60   74.71   74.85
 -924.33 -924.49 -924.64 -924.65 -924.76 -924.79 -924.80 -924.57 -924.62 -924.66
 -924.79 -924.83   72.17   71.72 -925.28 -925.48 -925.20 -925.28 -925.39 -925.52
 -925.40 -925.29 -925.15
BR Coef=-1 , 0 , 0 ,, 0 ,,,0.8,0,1,0,
WSPro=,,,, 1 ,,,, 0 ,,,, 0 ,,,,-1 ,-1 ,-1 , 0 , 0 , 0 , 0 , 0
BC Design=,, 0 ,, 0 ,,,,,,

Type RM Length L Ch R = 1 ,19223.87,238.465000,238.465000,238.465000
XS GIS Cut Line= 5
916179.207754813801176.905594459916142.315393702 800979.42295557
916170.527199258800905.638233348916211.759838146800814.492400014
916213.929977035800428.207677792
#Sta/Elev= 30
9666.612103.58029688.897 101.1639709.24395.378499719.41694.289329739.762 88.5901
9770.28187.857839810.97383.735289852.89281.281159893.659 75.68149931.02974.37513
9947.206 75.44039958.18274.446399969.15770.1923510002.0865.7598510013.0674.09279
10024.0475.6071110046.5473.8061910116.0476.1943710286.0474.7322610306.0476.23299
10326.0476.1601710336.0478.9931110346.0486.3727510356.0488.4259510376.04101.0213
10386.04101.319810396.04105.280910406.04111.298910416.04119.137510432.83129.0562
#Mann= 3 , 0 , 0
9666.612  0.0474       09666.612  0.0474       010432.83  0.0474       0
#XS Ineff= 2 , 0
       09848.722         10222.2       0
Bank Sta=9666.612,10432.83
Exp/Cntr=0.3,0.1