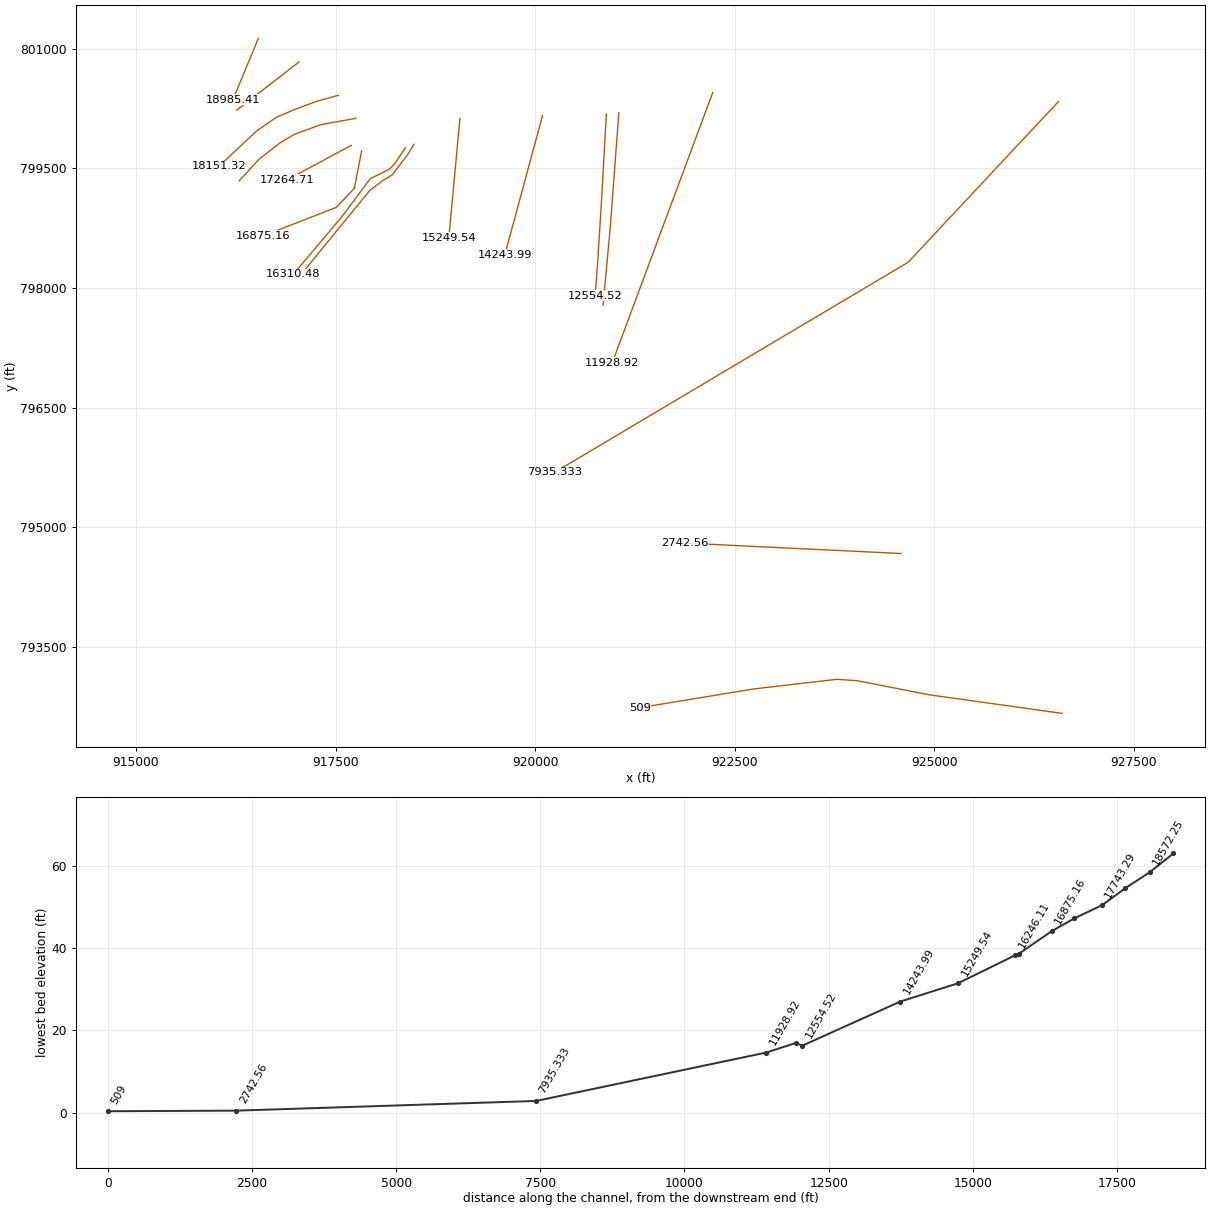
HEC-RAS study 13252_ras.prj: 13252

--- 13252_ras.g01 (geometry) --- (continued)

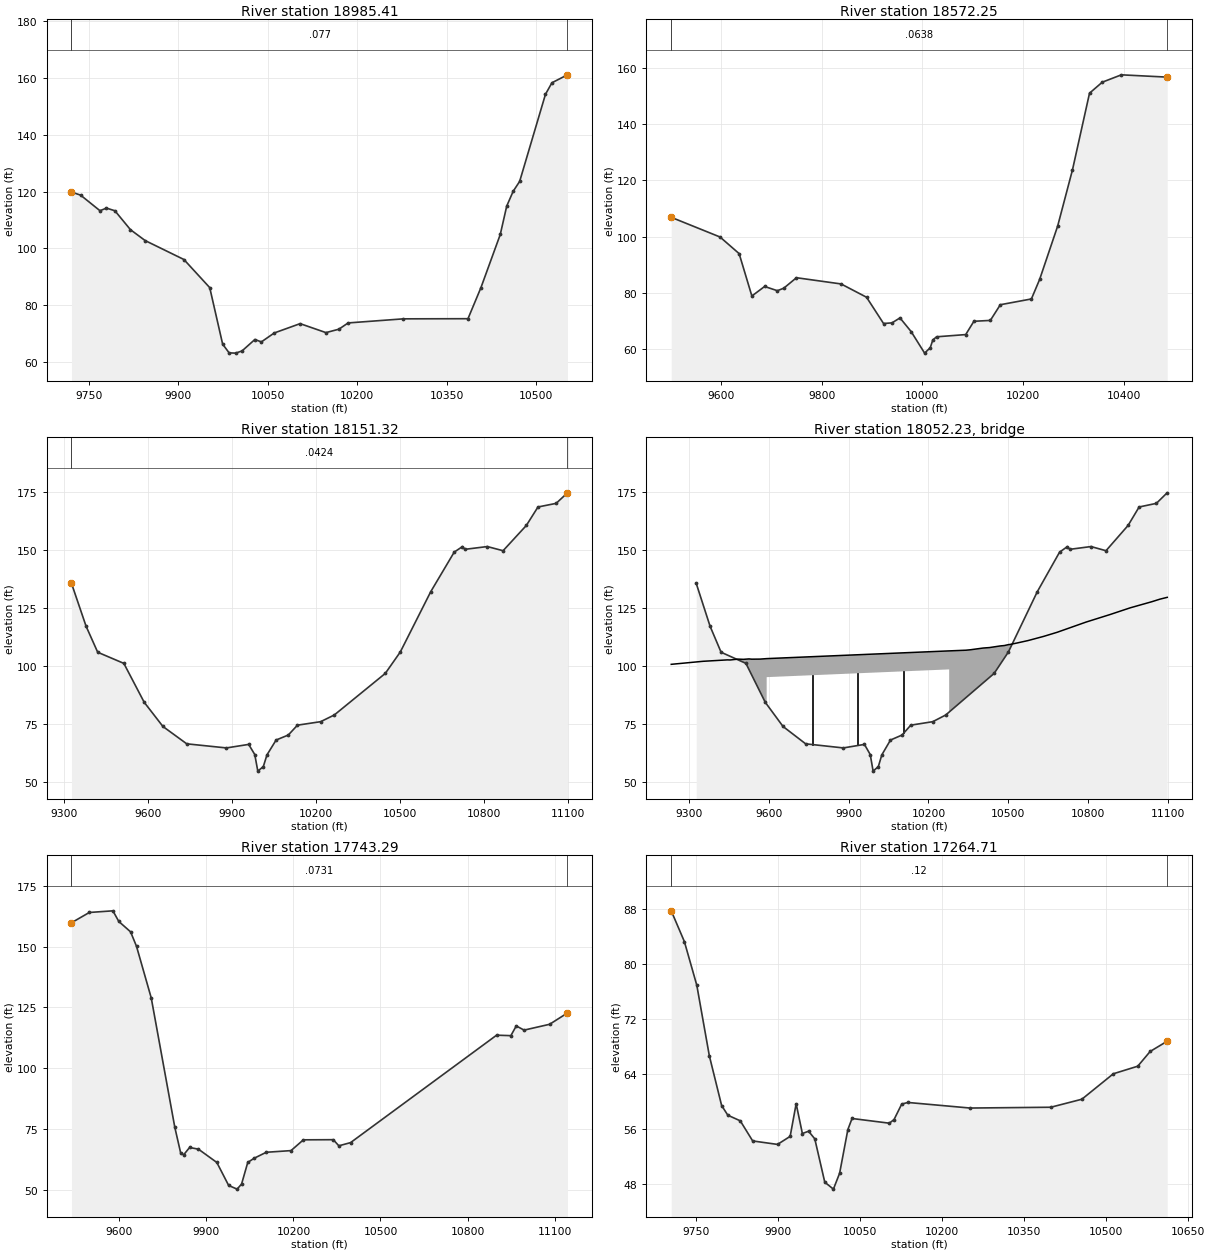
Type RM Length L Ch R = 1 ,18985.41,413.153000,413.153000,413.153000
XS GIS Cut Line= 2
916532.940393702801129.162538903916213.929977035800360.933372236
#Sta/Elev= 30
9720.962119.84859736.297118.75539768.781113.26269779.609114.18829793.818 113.246
9819.893106.57419844.576102.73569909.54496.060069952.85586.145319974.51166.21573
9985.33963.148699996.16763.0515610006.99  63.813 10028.567.8488110039.4867.01631
10061.1370.1647310104.4573.4469210147.7670.2836910169.4171.4848710184.9573.69792
10277.6975.1392810385.9775.1895810407.6386.1113110440.11104.883510450.94114.8964
10461.77120.1207 10472.6 123.58710515.91154.304910526.73158.373610552.79161.1732
#Mann= 3 , 0 , 0
9720.962   0.077       09720.962   0.077       010552.79   0.077       0
#XS Ineff= 2 , 0
       0                10287.33       0
Bank Sta=9720.962,10552.79
Exp/Cntr=0.3,0.1

Type RM Length L Ch R = 1 ,18572.25,420.929400,420.929400,420.929400
XS GIS Cut Line= 2
917041.566695785800833.481115292916263.029369396800229.639969459
#Sta/Elev= 30
9501.268106.86949598.16699.854259636.13293.929119661.44378.813919686.75382.21456
9712.06480.709259724.71981.59348 9750.0385.334939838.61783.118559889.23878.37771
9923.02269.01012 9939.8669.246129955.65571.008569977.82566.13595 10004.658.45466
10015.7960.3903610020.9263.1652410028.4564.2772510086.1965.06502 10102.569.80969
10135.1470.11521   1015575.7097910216.7277.7672810233.0484.71311 10268.9103.7609
 10298.3123.782210332.17151.123110357.48155.036910395.45157.664610486.53156.8453
#Mann= 3 , 0 , 0
9501.268  0.0638       09501.268  0.0638       010486.53  0.0638       0
#XS Ineff= 2 , 0
       0                10241.25       0
Bank Sta=9501.268,10486.53
Exp/Cntr=0.3,0.1

Type RM Length L Ch R = 1 ,18151.32,408.036400,408.036400,408.036400
XS GIS Cut Line= 6
917535.273293007800415.729379181917250.442563841800335.976775014
916958.016348563800225.842226403916756.735966619800138.494136126
916509.882668007799967.595698626916038.962529119799527.057504181
#Sta/Elev= 30
9325.528135.75049377.735117.19869419.273 105.9529512.735101.14019585.42784.34417
9652.45773.880269737.57566.387359879.43764.615259958.88266.138249980.68461.76741
9991.58554.5934310011.2756.5598610024.2961.6026710056.9968.02775 10100.670.19326
 10133.374.4487210216.1375.9549810264.76 78.832110447.2296.8077410500.85106.0582
10609.55132.0827 10693.6149.208610723.14151.601610731.85150.406410811.76151.6065
10868.27149.8089 10951.4160.727510992.97168.699811057.97170.268511098.34174.8175
#Mann= 3 , 0 , 0
9325.528  0.0424       09325.528  0.0424       011098.34  0.0424       0
#XS Ineff= 2 , 0
       0                               0
Bank Sta=9325.528,11098.34
Exp/Cntr=0.3,0.1

Type RM Length L Ch R = 3 ,18052.23,,,
BEGIN DESCRIPTION:
END DESCRIPTION:
Bridge Culvert--1,0,-1,-1, 0
Deck Dist Width WeirC Skew NumUp NumDn MinLoCord MaxHiCord MaxSubmerge Is_Ogee
148.018200,112.000000,2.6,0, 31, 33, , , 0.95, 0, 0,0,,
 9231.58 9351.52 9442.80 9452.94 9483.37 9503.65 9524.26 9534.77 9566.30 9590.86
 9590.8610277.8610277.8610340.7510357.6810405.9010429.6010469.7410485.7010501.40
10507.1010530.8310574.9810633.8410684.3010793.3410883.2610959.4211040.8011071.17
11098.77
  100.73  102.04  102.65  102.61  102.98  102.89  103.07  102.96  102.99  103.20
  103.20  106.54  106.54  106.83  107.02  107.77  107.97  108.67  108.85  109.26
  109.32  109.88  111.00  112.81  114.57  118.99  122.23  125.14  127.78  128.88
  129.67
 -899.27 -897.96 -897.35 -897.39 -897.02 -897.11 -896.93 -897.04 -897.01 -896.80
   95.20   98.54 -893.46 -893.17 -892.98 -892.23 -892.03 -891.33 -891.15 -890.74
 -890.68 -890.12 -889.00 -887.19 -885.43 -881.01 -877.77 -874.86 -872.22 -871.12
 -870.33
 9231.58 9351.52 9442.80 9452.94 9483.37 9503.65 9524.26 9534.77 9566.30 9587.32
 9595.01 9749.19 9749.1910328.6110357.6810405.9010429.6010436.1910436.1910469.74
10485.7010501.4010507.1010530.8310574.9810633.8410684.3010793.3410883.2610959.42
11040.8011071.1711098.77
  100.73  102.04  102.65  102.61  102.98  102.89  103.07  102.96  102.99  103.13
  103.26  104.00  104.00  106.73  107.02  107.77  107.97  108.11  108.11  108.67
  108.85  109.26  109.32  109.88  111.00  112.81  114.57  118.99  122.23  125.14
  127.78  128.88  129.67
 -899.27 -897.96 -897.35 -897.39 -897.02 -897.11 -896.93 -897.04 -897.01 -896.87
 -896.74 -896.00   96.00   98.73   99.02   99.77   99.97  100.11 -891.89 -891.33
 -891.15 -890.74 -890.68 -890.12 -889.00 -887.19 -885.43 -881.01 -877.77 -874.86
 -872.22 -871.12 -870.33
Pier Skew, UpSta & Num, DnSta & Num=  ,9761.61, 2 ,9919.94, 2 , 0 , 0 , 0 ,,
    4.00    4.00
 -895.94  104.06
    4.00    4.00
 -895.18  104.82
Pier Skew, UpSta & Num, DnSta & Num=  ,9934.36, 2 ,10092.69, 2 , 0 , 0 , 0 ,,
    4.00    4.00
 -895.11  104.89
    4.00    4.00
 -894.35  105.65
Pier Skew, UpSta & Num, DnSta & Num=  ,10107.11, 2 ,10265.44, 2 , 0 , 0 , 0 ,,
    4.00    4.00
 -894.28  105.72
    4.00    4.00
 -893.52  106.48
BR Coef=-1 , 0 , 0 ,, 0 ,,,0.8,0,1,0,
WSPro=,,,, 1 ,,,, 0 ,,,, 0 ,,,,-1 ,-1 ,-1 , 0 , 0 , 0 , 0 , 0
BC Design=,, 0 ,, 0 ,,,,,,

Type RM Length L Ch R = 1 ,17743.29,478.573900,478.573900,478.573900
XS GIS Cut Line= 6
 917755.54239023800127.100906959917315.004195785800047.348302792
916973.207320785799922.022781959 916798.51114023799815.685976403
916536.466869396799610.607851403916293.411313841799344.765837514
#Sta/Elev= 30
9435.198159.77569496.724163.99329578.025 164.668 9598.35160.3021    9639156.0271
9659.325150.09799710.138128.90079791.43875.730999811.76365.152389821.92664.52801
9842.25167.514479872.73866.825729936.15661.367129976.86351.9350110005.9150.42044
10021.36 52.486210042.6761.3561910063.9763.0490310106.57  65.55110191.78 66.2342
10234.3970.6587910337.3870.7151810356.6268.2060810397.0469.5137410900.21113.6164
10949.41113.425510967.96117.407510995.06115.697411082.78118.084511144.42122.7342
#Mann= 3 , 0 , 0
9435.198  0.0731       09435.198  0.0731       011144.42  0.0731       0
#XS Ineff= 2 , 0
       0                 10288.8       0
Bank Sta=9435.198,11144.42
Exp/Cntr=0.3,0.1

Type RM Length L Ch R = 1 ,17264.71,389.555800,389.555800,389.555800
XS GIS Cut Line= 2
917696.134838146 799788.01670557916897.523727035 799358.32920557
#Sta/Elev= 30
9704.74587.797479728.74483.322419751.45676.960949774.42766.666789796.87859.42626
9808.23358.012779830.94557.198919853.65654.265769899.078 53.76149922.16554.93154
9933.14559.68733  9944.5 55.34779955.85655.684299967.21254.570849985.48148.25409
10001.28 47.244810012.6349.5653210027.6955.9290510035.3457.5377610103.4856.85277
10112.1157.3792910126.1959.6435210137.5559.87231 10251.159.0604310398.7259.17659
 10455.560.3433410513.1164.05488 10557.765.1559710580.41 67.305910611.61 68.8013
#Mann= 3 , 0 , 0
9704.745    0.12       09704.745    0.12       010611.61    0.12       0
#XS Ineff= 2 , 0
       0                10176.28       0
Bank Sta=9704.745,10611.61
Exp/Cntr=0.3,0.1

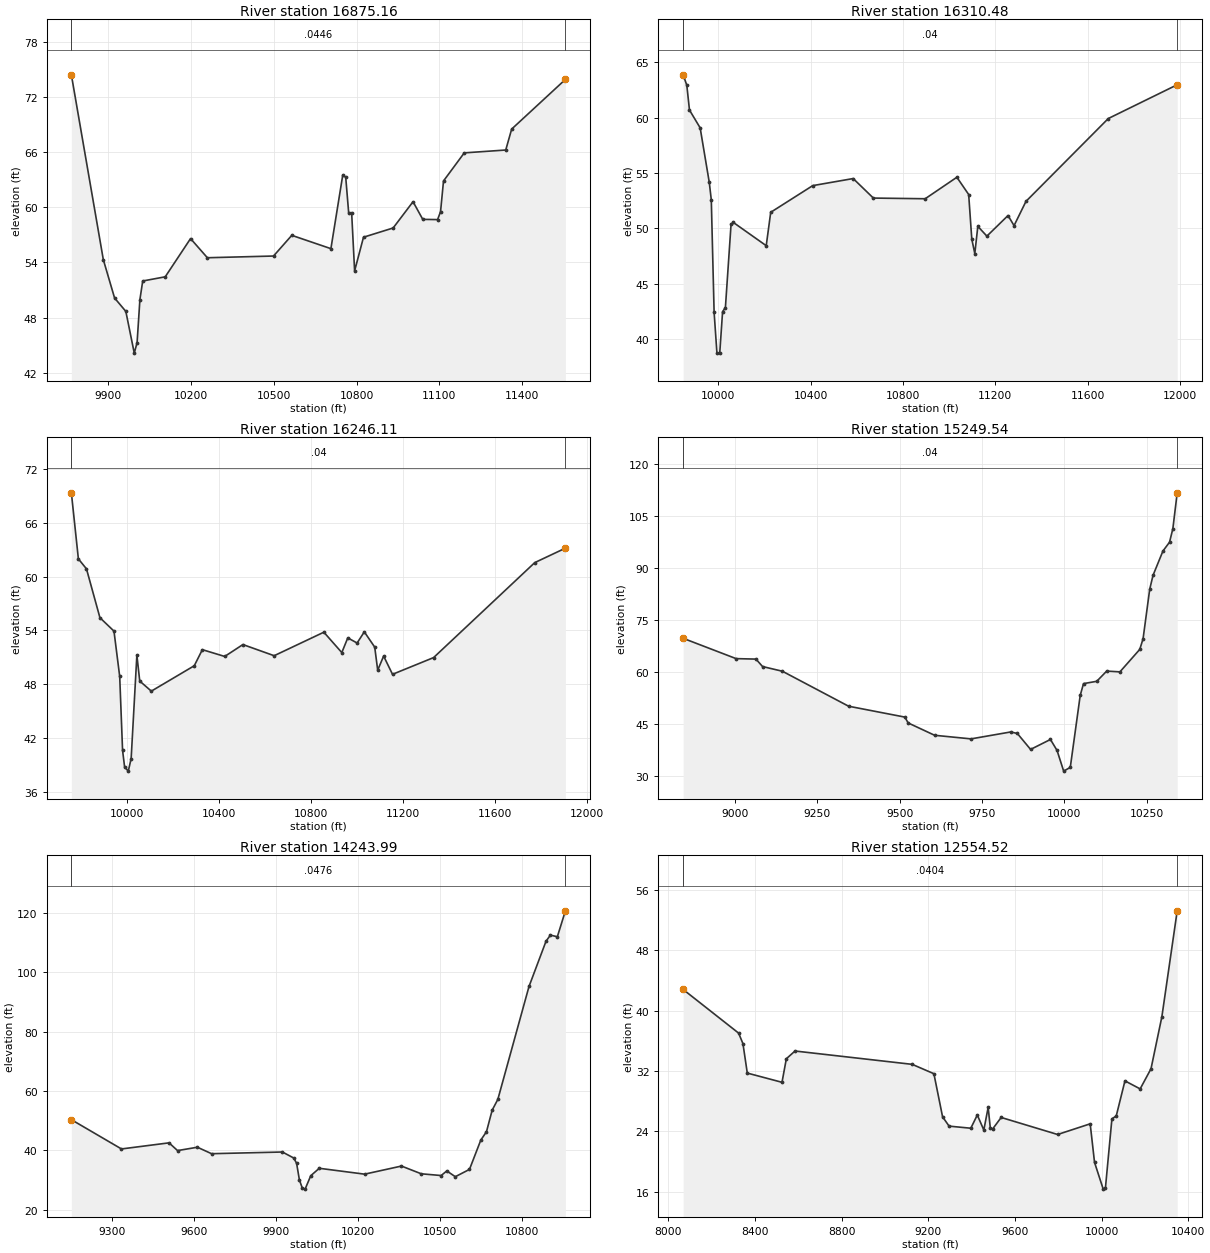
Type RM Length L Ch R = 1 ,16875.16,564.680400,564.680400,564.680400
XS GIS Cut Line= 4
 917826.34317148799718.572261126917735.197338146799249.822261125
917509.502893702799011.106983348916593.704282591 798655.20420557
#Sta/Elev= 30
9767.43974.385929883.13854.293599923.88750.128069964.63748.672439995.19844.13684
10005.3945.2816610015.5749.9554310025.7651.9769410107.2652.4322910198.9456.58694
10259.8154.5050310499.3254.6908810565.4856.9396610707.0655.4922610749.97 63.4883
 10760.763.2597610771.43 59.374610782.1659.4029310792.8953.0742710825.0756.73556
10932.3657.7389111004.4460.5945311039.6558.6757811093.2958.6497811104.0259.51201
11114.7562.8507611189.8565.9028811340.0566.21321 11361.568.4887211556.0173.88597
#Mann= 3 , 0 , 0
9767.439  0.0446       09767.439  0.0446       011556.01  0.0446       0
#XS Ineff= 2 , 0
       0                10131.81       0
Bank Sta=9767.439,11556.01
Exp/Cntr=0.3,0.1

Type RM Length L Ch R = 1 ,16310.48,64.367400,64.367400,64.367400
XS GIS Cut Line= 6
918373.871560652799758.592021909918254.434367393799576.081254682
918175.256902199 799490.19383481 917933.69853381799369.414650615
  917577.4918963798891.927365209916972.563662892798174.761518153
#Sta/Elev= 30
9848.211 63.88449863.93762.940939875.50660.700069921.78459.086029961.28154.15489
9970.02252.57589 9982.2542.399749994.47838.7101210006.7138.7380310018.9342.45961
10031.1642.8327310055.6250.3522110065.5450.5317310208.01 48.428610227.4551.44786
10409.4853.8623910584.7554.5016810672.0952.7362510896.6652.6747311033.89 54.6192
11085.0953.0566511098.5149.0280111111.59 47.716211124.6850.1795511163.9249.29286
 11255.551.1566611281.67 50.243411333.24 52.437611689.9659.9320811988.4362.98659
#Mann= 3 , 0 , 0
9848.211    0.04       09848.211    0.04       011988.43    0.04       0
#XS Ineff= 2 , 0
       0                10075.08       0
Bank Sta=9848.211,11988.43
Exp/Cntr=0.3,0.1

Type RM Length L Ch R = 1 ,16246.11,996.571800,996.571800,996.571800
XS GIS Cut Line= 6
918481.725115924799801.037538903918407.940393702799679.509761126
918210.457754813799419.093094459918106.291088146799356.159066681
917930.509838146799225.950733348917084.744533501798191.588648745
#Sta/Elev= 30
9759.83269.353269790.29361.98479 9825.3960.875129883.88455.423439944.90553.92515
9969.76748.867419982.19840.627529991.12438.7596610007.0638.3083510019.4939.70815
10044.3551.2520210056.7948.3567810107.1247.2308810293.6650.0652710328.7151.85772
10425.8951.1002610504.86 52.427910640.6251.1830610856.4453.8062310934.4151.53269
10960.3953.1749811000.8252.5975711032.1453.8447611077.3452.1418711090.3149.57017
11116.0551.1424511154.6649.1079511333.18 50.9753 11772.461.5685611905.4963.17934
#Mann= 3 , 0 , 0
9759.832    0.04       09759.832    0.04       011905.49    0.04       0
#XS Ineff= 2 , 0
       0                10066.59       0
Bank Sta=9759.832,11905.49
Exp/Cntr=0.3,0.1

Type RM Length L Ch R = 1 ,15249.54,1005.548900,1005.548900,1005.548900
XS GIS Cut Line= 2
919058.168258286800124.930768071918919.279369397798631.875212515
#Sta/Elev= 30
 8843.0569.728249003.67163.87799 9063.9363.741489084.017 61.59579144.27660.24165
9345.13950.168729515.87347.035949525.91645.352939606.26241.796149716.73740.75991
9837.25542.754979857.34142.318929897.51437.724889957.77340.591999977.85937.43252
9997.945 31.471610018.0332.5552910048.1653.28625 10058.2 56.678710098.3857.34766
10128.5160.2860210168.6860.0633410228.9466.5407910238.9869.6114710259.0783.84443
10269.1187.8518110299.2494.8689110319.3397.4274310329.37101.323510342.55 111.636
#Mann= 3 , 0 , 0
 8843.05    0.04       0 8843.05    0.04       010342.55    0.04       0
#XS Ineff= 2 , 0
       0                               0
Bank Sta=8843.05,10342.55
Exp/Cntr=0.3,0.1

Type RM Length L Ch R = 1 ,14243.99,1689.465700,1689.465700,1689.465700
XS GIS Cut Line= 2
920092.890480508800159.652990293919620.668258286798416.597434737
#Sta/Elev= 30
9152.76450.372759335.90940.517119509.84142.572119540.92339.965679613.44641.09541
9665.24838.92022 9924.2639.487619965.70237.463589976.06335.699959986.42330.05664
9996.78427.3970510007.1426.9966310027.8731.5124510058.9534.0107310224.7132.03377
 10359.434.7600510431.92 32.154110504.4531.5743510525.1733.1199210556.2531.17685
10608.0533.6409610649.4943.5147710670.2246.3235310690.94  53.55810711.6657.19364
10825.6295.1917110887.79110.421110903.85112.479610929.23111.934310958.65120.6556
#Mann= 3 , 0 , 0
9152.764  0.0476       09152.764  0.0476       010958.65  0.0476       0
#XS Ineff= 2 , 0
       0                               0
Bank Sta=9152.764,10958.65
Exp/Cntr=0.3,0.1

Type RM Length L Ch R = 1 ,12554.52,118.128100,118.128100,118.128100
XS GIS Cut Line= 4
 920893.23770273800180.486323626 920830.73770273799065.902990293
 920783.86270273798321.111323626 920752.61270273 797904.44465696
#Sta/Elev= 30
8068.88642.805648324.77437.020588344.80535.621688364.83731.718918525.08830.49544
8545.11933.621148585.18234.64585 9126.0332.877059226.20431.635359266.28325.91653
9296.34324.681879396.541 24.4038  9426.626.157969456.65924.162339476.69927.17132
9486.71924.406889496.73824.283549536.81825.831479797.33223.572639947.64224.98756
9967.69819.8771310007.8116.3257610017.8416.4256810047.9225.6451810067.9826.03761
10108.0930.6839710178.2929.6213410228.43 32.296810278.5739.1964310349.3253.24091
#Mann= 3 , 0 , 0
8068.886  0.0404       08068.886  0.0404       010349.32  0.0404       0
#XS Ineff= 2 , 0
       0 9897.02         10117.7       0
Bank Sta=8068.886,10349.32
Exp/Cntr=0.3,0.1

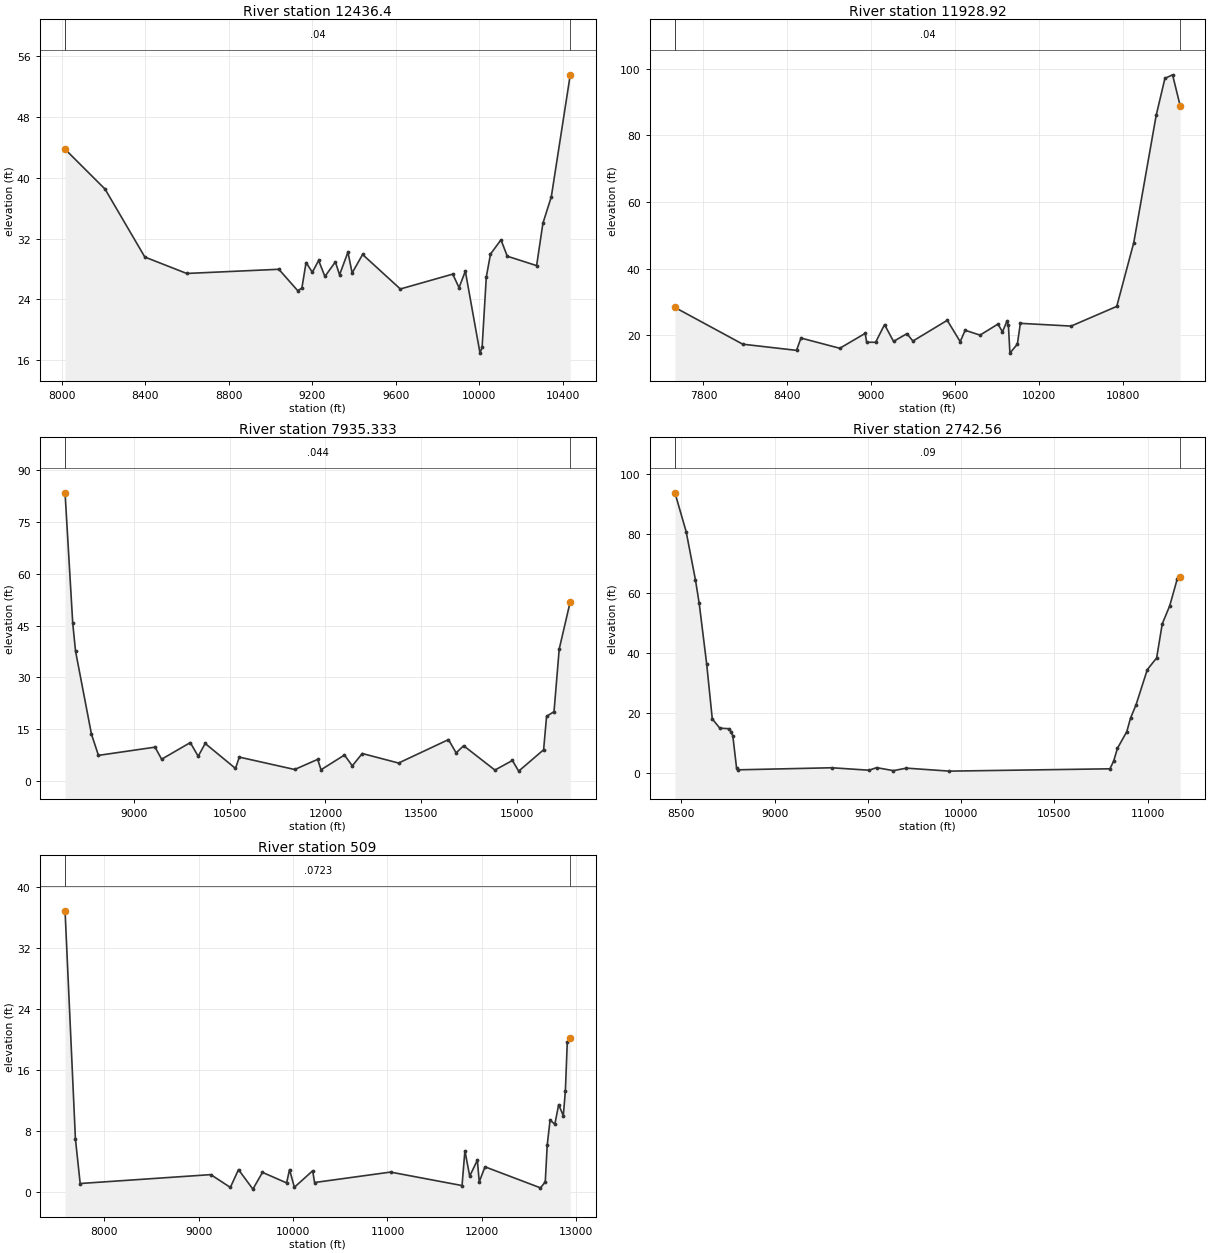
Type RM Length L Ch R = 1 , 12436.4,507.474600,507.474600,507.474600
XS GIS Cut Line= 3
 921049.48770273800196.111323626 920940.11270273798737.777990293
920851.571036063797784.652990293
#Sta/Elev= 30
8016.79943.750948208.44738.504968398.98129.572658599.54327.416999040.77827.96639
9131.03125.159099151.08725.491549171.14428.854089201.22827.574019231.312 29.1275
9261.396 27.02119311.53728.933629331.59327.237859371.70530.220649391.76127.48096
9441.90229.910919622.62125.376499873.69827.332389903.82725.548689933.95627.72044
10004.2616.94431 10014.3 17.707310034.3926.9432110054.4729.9673210104.6931.83839
10134.8229.6850810275.4228.4467210305.5534.0246510345.7237.4916610436.4653.52809
#Mann= 3 , 0 , 0
8016.799    0.04       08016.799    0.04       010436.46    0.04       0
#XS Ineff= 2 , 0
       09915.938           10069       0
Bank Sta=8016.799,10436.46
Exp/Cntr=0.3,0.1

Type RM Length L Ch R = 1 ,11928.92,3993.588100,3993.588100,3993.588100
XS GIS Cut Line= 2
922225.702980508800449.583545849920967.022424952797064.166879182
#Sta/Elev= 30
7596.56828.339998081.55417.31938 8465.63 15.46918497.637 19.16068775.02516.09283
8956.39520.564938967.06417.900689031.07617.895559095.08923.194389159.10218.15844
9255.12120.480639297.79618.257689543.17924.487119635.95718.081349671.20421.50252
9777.89220.041549905.91723.363449937.92421.01072 9969.9324.211019980.59922.98609
9991.26814.6395410044.6117.3445110065.9523.5777810428.6922.7542410755.0828.65827
10876.78 47.805411036.8185.9381411099.4297.0592411154.1798.12949 11208.488.86397
#Mann= 3 , 0 , 0
7596.568    0.04       07596.568    0.04       0 11208.4    0.04       0
#XS Ineff= 2 , 0
       09537.541        10083.94       0
Bank Sta=7596.568,11208.4
Exp/Cntr=0.3,0.1

Type RM Length L Ch R = 1 ,7935.333,5192.772700,5192.772700,5192.772700
XS GIS Cut Line= 3
 926557.30020273800336.736323626924673.619647175798322.847434738
920246.536313841795692.639101404
#Sta/Elev= 30
7924.259 83.42658044.73945.629588088.65737.564018337.52113.565988446.955 7.42054
9332.9789.8044379435.452 6.306939884.67711.1256410007.917.15887610117.4510.86458
10591.943.63977710651.466.92075611517.673.33271611878.266.26413411930.583.252735
   122977.52191812420.044.39547412576.16 7.9605313144.435.20262513925.45 11.9895
14045.038.144461 14162.510.2161614651.953.16739614925.785.94248715023.942.860777
15414.319.04381815460.8418.7372415577.16 20.069115658.5838.2128715831.2751.93622
#Mann= 3 , 0 , 0
7924.259   0.044       07924.259   0.044       015831.27   0.044       0
#XS Ineff= 2 , 0
       0                12376.61       0
Bank Sta=7924.259,15831.27
Exp/Cntr=0.3,0.1

Type RM Length L Ch R = 1 , 2742.56,2233.560400,2233.560400,2233.560400
XS GIS Cut Line= 2
924584.925653451794674.223177593921879.059809768794804.483677726
#Sta/Elev= 30
8465.83993.639638525.83480.666418575.89264.447028595.91556.626858635.96136.34675
8665.99617.986198706.04214.90485  8756.114.686778766.11213.704478776.123 12.3178
8796.1471.6004538806.1580.9482229306.737 1.634089506.969 0.809019547.0151.678412
9637.1190.672499  9707.21.5075499937.4670.50708810798.46 1.2857710818.493.907935
10838.518.15053910888.5713.6963210908.5918.2076510938.6222.7672910998.69 34.4777
11048.7538.3926211078.7949.7877811118.8355.8263611158.8864.7391611174.84 65.3852
#Mann= 3 , 0 , 0
8465.839    0.09       08465.839    0.09       011174.84    0.09       0
#XS Ineff= 2 , 0
       0                               0
Bank Sta=8465.839,11174.84
Exp/Cntr=0.3,0.1

Type RM Length L Ch R = 1 ,     509,0.000000,0.000000,0.000000
XS GIS Cut Line= 6
926603.798091301792670.917238431 924935.02676114792904.272316341
924035.621842307793080.337935644923783.605536412793097.821541337
922742.055185703792977.315416842921313.989029853792743.112567283
#Sta/Elev= 30
7585.36636.877957695.1196.9628287745.558 1.099119128.8352.2650459336.1310.587836
9422.4752.9241879574.775 0.361869676.4392.5631049932.0161.1772389962.882 2.92738
10014.320.60765810207.952.76867510228.071.22791811032.382.59879811789.940.830594
11820.355.40078811871.012.07128611952.08  4.153911972.351.31958712033.153.289445
 12620.90.52808312671.571.32036912691.836.10651612722.239.408033 12772.98.888857
12813.4411.4492712862.619.99624812884.3713.2568112904.6419.6593512936.0620.17417
#Mann= 3 , 0 , 0
7585.366  0.0723       07585.366  0.0723       012936.06  0.0723       0
#XS Ineff= 2 , 0
       0                               0
Bank Sta=7585.366,12936.06
Exp/Cntr=0.3,0.1